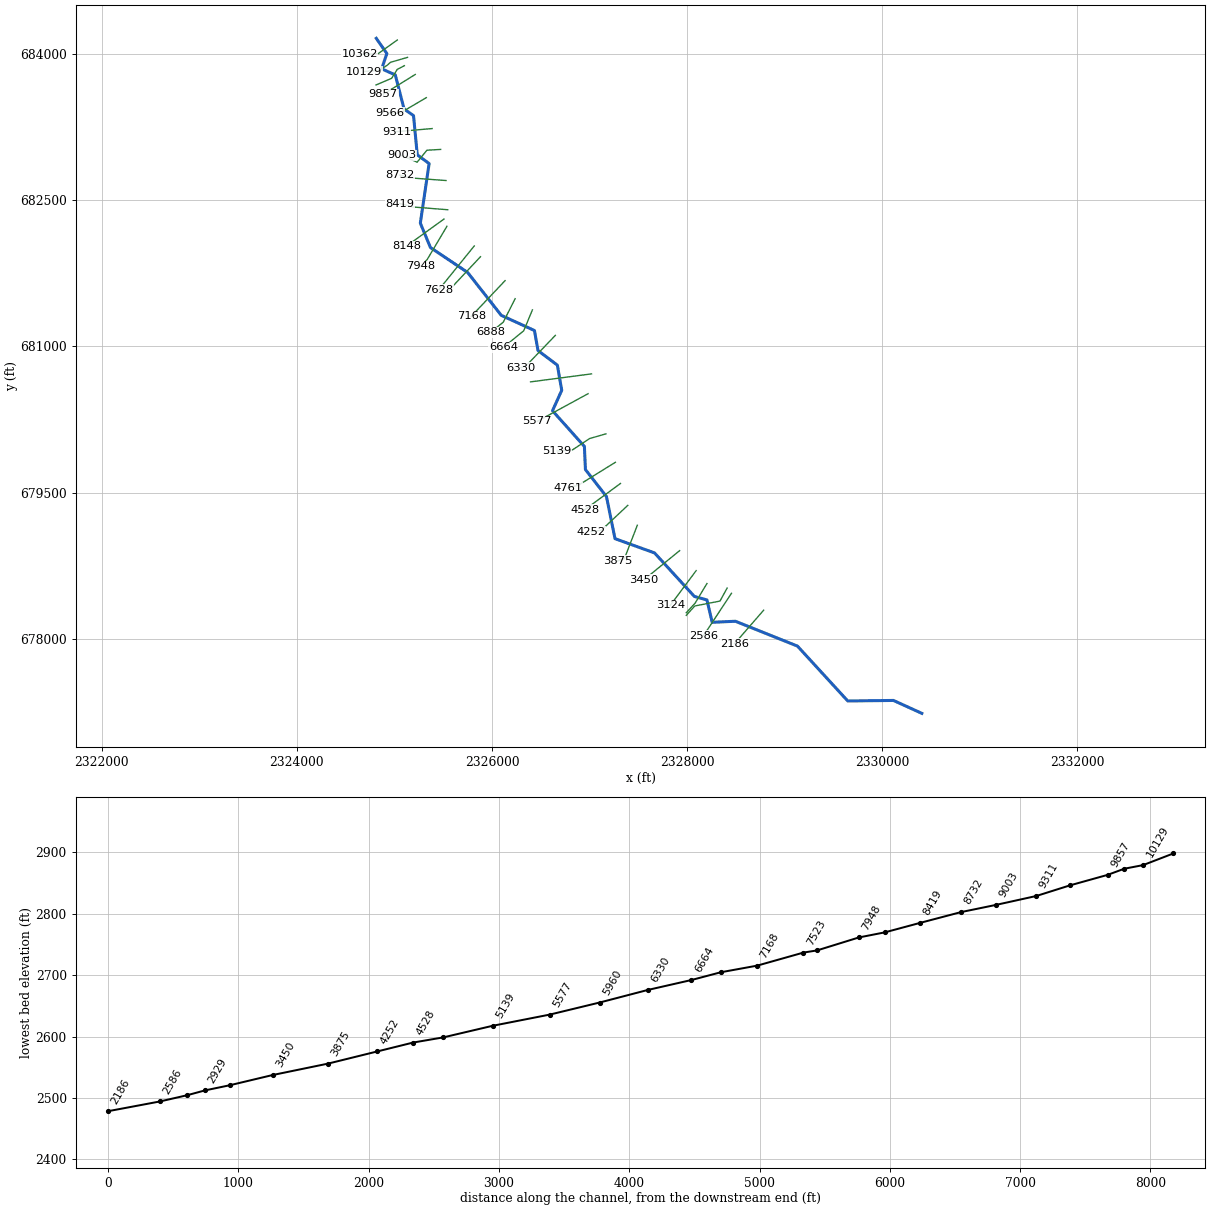
--- UPPRPNDLCK.prj (project) ---

Proj Title=UPPRPNDLCK
Current Plan=p01
Default Exp/Contr=0,0
English Units
Geom File=g01
Flow File=f01
Plan File=p01
Background Map Layer=Inundation Boundary (P100yr Value_0)
BEGIN DESCRIPTION:
----------MODEL BY WOOD PLC 2022----------
AFH study
Randolph County, WV
HEC-RAS Version: RAS 6.2
Vertical Datum: NAVD88
Projection: NAD 1983 StatePlane West Virginia S FIPS 4702 (US Feet)
Terrain: 1-meter LIDAR (FEMA Region III 3DEP collected 2016-2018)
Land Use: 2019 NLCD
Hydrologic Method:
WV SIR2010-5033 regression equations
Additional Model Notes:
None
END DESCRIPTION:
DSS Export Rating Curves= 0
DSS Export Rating Curve Sorted= 0
DSS Export Volume Flow Curves= 0
DXF OffsetX= 0
DXF OffsetY= 0
DXF ScaleX= 0
DXF ScaleY= 0

--- UPPRPNDLCK.p01 (plan) ---

Plan Title=Floodplain
Program Version=6.20
Short Identifier=Floodplain
Geom File=g01
Flow File=f01
Subcritical Flow
K Sum by GR= 0
Std Step Tol= 0.01
Critical Tol= 0.01
Num of Std Step Trials= 20
Max Error Tol= 0.3
Flow Tol Ratio= 0.001
Split Flow NTrial= 30
Split Flow Tol= 0.02
Split Flow Ratio= 0.02
Log Output Level= 0
Friction Slope Method= 1
Unsteady Friction Slope Method= 2
Unsteady Bridges Friction Slope Method= 1
Parabolic Critical Depth
Global Vel Dist= 0 , 0 , 0
Global Log Level= 0
CheckData=True
Encroach Param=-1 ,0,0, 0
Mapping Interval=1HOUR
Computation Time Step Use Courant=        0
Computation Time Step Use Time Series=    0
Computation Time Step Count To Double=0
Computation Time Step Max Doubling=0
Computation Time Step Max Halving=0
Computation Time Step Residence Courant=0
Run HTab= 0
Run UNet= 0
Run Sediment= 0
Run PostProcess= 0
Run WQNet= 0
Run RASMapper=-1
UNET Theta= 0
UNET Theta Warmup= 0
UNET ZTol= 0
UNET ZSATol= 0
UNET MxIter= 0
UNET Max Iter WO Improvement= 0
UNET MaxInSteps= 0
UNET DtIC= 0
UNET DtMin= 0
UNET MaxCRTS= 0
UNET WFStab= 0
UNET SFStab= 0
UNET WFX= 1
UNET SFX= 1
UNET Gravity=32.174
UNET 1D Methodology=Finite Difference
UNET DSS MLevel= 1
UNET Pardiso=0
UNET DZMax Abort= 0
UNET Use Existing IB Tables= 0
UNET Froude Reduction=False
UNET Froude Limit= 0
UNET Froude Power= 0
UNET D1 Cores= 0
UNET WindReference=Eulerian
UNET WindDragFormulation=Hsu (1988)
UNET D2 Coriolis=0
UNET D2 Cores= 0
UNET D2 Theta= 1
UNET D2 Theta Warmup= 1
UNET D2 Z Tol= 0.01
UNET D2 Volume Tol= 0.01
UNET D2 Max Iterations= 20
UNET D2 Equation= 0
UNET D2 RampUpFraction=0.1
UNET D2 TimeSlices= 1
UNET D2 Turbulence Formulation=Non-Conservative (original)
UNET D2 Eddy Viscosity=0.3
UNET D2 Transverse Eddy Viscosity=0.1
UNET D2 Smagorinsky Mixing=0
UNET D2 BCVolumeCheck=0
UNET D2 Cores=0
UNET D2 SolverType=PARDISO (Direct)
UNET D2 Minimum Iterations= 2147483647
UNET D2 Maximum Iterations= 2147483647
UNET D2 Restart Number= 10
UNET D2 Relaxation Coeff=1.3
UNET D2 SOR Precondition Iterations= 10
UNET D2 ILUT Maximum Fill= 8
UNET D2 ILUT Tolerance=1E-08
UNET D1D2 MaxIter= 0
UNET D1D2 ZTol=0.01
UNET D1D2 QTol=0.1
UNET D1D2 MinQTol=1
Write IC File= 0
Write IC File at Fixed DateTime=0
Write IC File at Sim End=0
Echo Input=False
Echo Parameters=False
Echo Output=False
Write Detailed= 0
HDF Write Warmup=0
HDF Write Time Slices=0
HDF Flush=0
HDF Compression= 1
HDF Chunk Size= 1
HDF Spatial Parts= 1
HDF Use Max Rows=0
HDF Fixed Rows= 1
Calibration Method= 0
Calibration Iterations= 20
Calibration Max Change=0.05
Calibration Tolerance=0.2
Calibration Maximum=1.5
Calibration Minimum=0.5
Calibration Optimization Method= 1
WQ AD Non Conservative
WQ ULTIMATE=-1
WQ Max Comp Step=1HOUR
WQ Output Interval=15MIN
WQ Output Selected Increments= 0
WQ Output face flow=0
WQ Output face velocity=0
WQ Output face area=0
WQ Output face dispersion=0
WQ Output cell volume=0
WQ Output cell surface area=0
WQ Output cell continuity=0
WQ Output cumulative cell continuity=0
WQ Output face conc=0
WQ Output face dconc_dx=0
WQ Output face courant=0
WQ Output face peclet=0
WQ Output face adv mass=0
WQ Output face disp mass=0
WQ Output cell mass=0
WQ Output cell source sink temp=0
WQ Output nsm pathways=0
WQ Output nsm derived pathways=0
WQ Create Restart=0
WQ Fixed Restart=0
WQ System Summary=0
WQ Write To DSS=0
Sorting and Armoring Iterations= 10
XS Update Threshold= 0.02
Bed Roughness Predictor= 0
Hydraulics Update Threshold= 0.02
Energy Slope Method= 1
Volume Change Method= 1
Sediment Retention Method= 0
Sediment TS Multiplier= 1
Warm Up Method= 0
XS Weighting Method= 0
Number of US Weighted Cross Sections= 1
Number of DS Weighted Cross Sections= 1
Upstream XS Weight=0
Main XS Weight=1
Downstream XS Weight=0
Number of DS XS's Weighted with US Boundary= 1
Upstream Boundary Weight= 1
Weight of XSs Associated with US Boundary= 0
Number of US XS's Weighted with DS Boundary= 1
Downstream Boundary Weight= 0.5
Weight of XSs Associated with DS Boundary= 0.5
Percentile Method= 0
Sediment Output Level= 3
Mass or Volume Output= 0
Output Increment Type= 1
Profile and TS Output Increment= 1
Transport Output Increment 1
XS Output Flag= 0
XS Output Increment= 10
Read HDF5 Sediment Hotstart= 0
Sediment Hotstart Type= 0
Write Gradation File= 0
Read Gradation Hotstart= 0
Write HDF5 File= 1
Write Binary Output= 1
Write DSS Sediment File= 0
DSS Sediment Output Type= 1
SV Curve= 0
Specific Gage Flag= 0
Subcell Erosion Methods= 0
Subcell Deposition Methods= 0
Advection Scheme= 1
Matrix Solver= 0
Implicit Weighting Factor= 1
Maximum Outer Loop Convergence Iterations= 5
Convergence Maximum Absolute= 0.001
Convergence RMSE= 0.0001
Grain Fractions Max Abs Error= 0.001
Max Subgrid Regions= 1
Max Subgrid Length Scale= 3.402823E+38
Initial Layer Thickness= 3.402823E+38
Min Layer Thickness= 3.402823E+38
Max Layer Thickness= 3.402823E+38
Number of Layers= 5

--- UPPRPNDLCK.f01 (steady flow) ---

Flow Title=Flow
Program Version=6.20
Number of Profiles= 1
Profile Names=P100yr
River Rch & RM=UPPRPNDLCK,Main,10362
     341
River Rch & RM=UPPRPNDLCK,Main,8419
     455
River Rch & RM=UPPRPNDLCK,Main,6664
     507
River Rch & RM=UPPRPNDLCK,Main,5577
     565
River Rch & RM=UPPRPNDLCK,Main,4252
     645
Boundary for River Rch & Prof#=UPPRPNDLCK,Main            , 1
Up Type= 0
Dn Type= 3
Dn Slope=0.0369
DSS Import GetInterval= 0
DSS Import GetPeak= 0
DSS Import FillOption= 0

--- UPPRPNDLCK.g01 (geometry) ---

Geom Title=Geometry
Program Version=6.20

River Reach=UPPRPNDLCK      ,Main
Reach XY= 30
2324814.53508685684156.5934942692324923.08651367684001.089963148
2324870.28100003683844.0180000222325009.60632412683781.552431606
2325099.44700003683432.1260000022325196.23599999683364.851999998
2325234.86400002682962.9420000022325356.21800002682873.359000012
2325266.11400001682262.942000017     2325369.868682012.290999994
2325750.47603975681757.767662228     2326095.476681317.976999998
2326435.57999998681162.2470000092326472.03900003680957.039000005
2326670.47600003680807.5600000172326715.26800002680549.747999996
2326620.69300003680340.0250000062326947.44800003679974.489000008
2326958.04200003679737.106000021     2327173.499679460.978000015
2327261.20300001679029.2329999952327666.12700002678883.153000012
2328074.87399998678436.7880000172328203.12800005678401.389000013
2328257.15422259678172.006489688     2328494.693678182.957000002
2329131.28100002677927.9300000072329646.31503349677365.973234191
     2330114.733677371.4030000122330405.90108405 677238.85431694

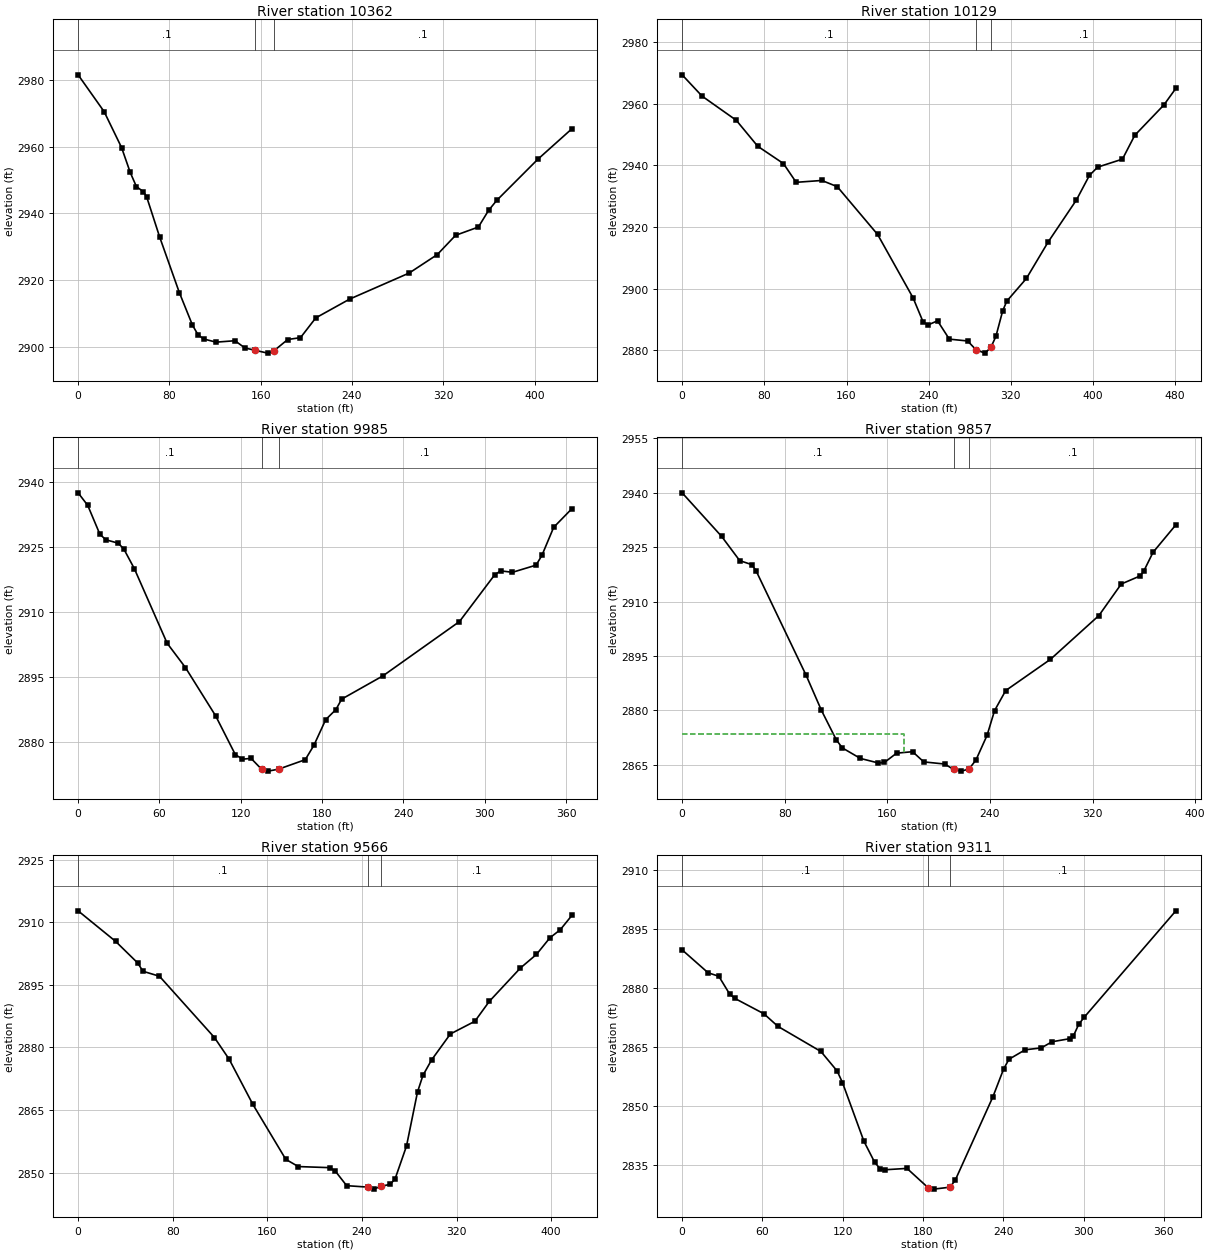
Type RM Length L Ch R = 1 ,10362   ,230,233.1,227.3
XS GIS Cut Line= 3
2325029.81950701684139.2983166332324831.90913231683998.330576052
2324642.33182601683991.386352378
#Sta/Elev= 30
       0 2981.44    22.8 2970.44    38.1 2959.69    45.7 2952.23    51.1 2948.01
    57.2  2946.5    60.1 2944.93    71.5 2932.91    88.7 2916.34   100.2  2906.6
   105.1 2903.69   110.1 2902.44   120.9 2901.49   137.5 2901.92   146.1 2899.77
   155.3 2899.04   166.2 2898.21   171.9 2898.98   183.7 2902.28   194.9 2902.84
   208.3 2908.75   238.1 2914.39   290.2 2922.17   314.8 2927.69   330.8 2933.44
   350.8 2935.92   359.7 2940.88   366.8 2943.86   402.8 2956.16432.6868 2965.29
#Mann= 3 ,-1,0
       0      .1       0   155.3    .045       0   171.9      .1       0
Bank Sta=155.3,171.9
XS Rating Curve= 0 ,0
Exp/Cntr(USF)=0,0
Exp/Cntr=0.3,0.1

Type RM Length L Ch R = 1 ,10129   ,139.8,144.2,146.2
XS GIS Cut Line= 6
2325134.84060859683961.5226300532324960.60586362683911.064597151
2324926.90459651683881.1166993782324854.36849323683832.468296654
2324776.67376592683824.3288906222324688.35364357683816.336127762
#Sta/Elev= 30
       0 2969.32    19.4 2962.42    52.7 2954.59    73.6 2946.17    98.6 2940.57
     111 2934.49     136 2935.09     151 2933.08   190.3 2917.58   224.8 2897.05
   234.6 2889.22   239.4 2888.28   248.6 2889.61   260.1 2883.67   277.9 2883.08
   286.1 2880.22   294.7 2879.14   300.5 2880.97   305.4 2884.54     312  2892.8
     316 2895.98   335.1 2903.33   356.2 2915.11   383.8 2928.77   396.5 2936.76
   404.5 2939.41   428.6    2942   440.6 2949.72     469 2959.58   480.6 2964.94
#Mann= 3 ,-1,0
       0      .1       0   286.1    .045       0   300.5      .1       0
Bank Sta=286.1,300.5
XS Rating Curve= 0 ,0
Exp/Cntr(USF)=0,0
Exp/Cntr=0.3,0.1

Type RM Length L Ch R = 1 ,9985    ,128.9,127.8,122.5
XS GIS Cut Line= 4
2325102.45804351683876.301023839 2325029.8273214683838.568173543
2324972.11557049683746.8538414432324811.86062282 683678.86906755
#Sta/Elev= 30
       0 2937.46     7.1 2934.57    16.1 2927.88    20.6 2926.62    29.6 2925.85
    33.7 2924.52    41.5 2919.97    65.7 2902.77    79.2 2897.16   101.5 2886.01
     116 2877.09   121.3 2876.02   127.6 2876.22   135.5 2873.67   140.2 2873.27
   147.9 2873.72   167.6 2875.91     174 2879.23   182.7 2885.15   190.2 2887.46
   194.5 2889.88     225 2895.26   281.4 2907.77   307.5  2918.6   311.8 2919.46
   320.5 2919.13   337.9 2920.78   342.2 2923.01   350.9  2929.5   364.3 2933.79
#Mann= 3 ,-1,0
       0      .1       0   135.5    .045       0   147.9      .1       0
Bank Sta=135.5,147.9
XS Rating Curve= 0 ,0
Exp/Cntr(USF)=0,0
Exp/Cntr=0.3,0.1

Type RM Length L Ch R = 1 ,9857    ,289.1,291,288.8
XS GIS Cut Line= 2
 2325214.3822879683786.3153821062324886.89269944683583.821819773
#Sta/Elev= 30
       0    2940    30.8 2927.98    44.9  2921.3    54.3  2920.2    57.6 2918.54
    96.7 2889.67   108.6 2880.03   120.2 2871.89   124.9 2869.66     139 2866.75
   153.1 2865.49   157.8 2865.66   167.2  2868.2   179.7 2868.61   188.4  2865.8
   204.8  2865.2   211.7 2863.71   217.5 2863.25   223.6 2863.79   229.1 2866.31
   237.8 2873.14   243.6 2879.92   252.3 2885.46   287.2 2894.08     325 2906.16
   342.4 2914.85     357 2917.06   359.9 2918.35   367.2 2923.59     385 2931.17
#Mann= 3 ,-1,0
       0      .1       0   211.7    .045       0   223.6      .1       0
#XS Ineff= 2 , 0
          172.75 2873.57
Permanent Ineff=
       F       F
Bank Sta=211.7,223.6
XS Rating Curve= 0 ,0
Exp/Cntr(USF)=0,0
Exp/Cntr=0.3,0.1

Type RM Length L Ch R = 1 ,9566    ,257.7,255.4,251.5
XS GIS Cut Line= 3
2325327.50369155683548.8229324572325052.51243406683386.953078617
2324954.39055355683393.827860054
#Sta/Elev= 30
       0 2912.77    31.7 2905.45    50.3 2900.29    54.9 2898.27    68.8 2897.08
   115.3 2882.38   127.8 2877.15   147.8 2866.34   175.6 2853.18   186.2 2851.44
   212.7 2851.18   217.4 2850.38   227.1 2846.86   245.2 2846.51   249.9 2846.03
   256.4 2846.72   263.8 2847.17     268 2848.45   277.7 2856.36     287 2869.32
   291.6 2873.31   298.9 2877.01   314.8 2883.24   335.5 2886.28   347.7 2891.05
     374 2899.05   387.6 2902.32     399 2906.31   407.7 2908.23   417.5 2911.65
#Mann= 3 ,-1,0
       0      .1       0   245.2    .045       0   256.4      .1       0
Bank Sta=245.2,256.4
XS Rating Curve= 0 ,0
Exp/Cntr(USF)=0,0
Exp/Cntr=0.3,0.1

Type RM Length L Ch R = 1 ,9311    ,301.2,307.3,312.4
XS GIS Cut Line= 2
2325387.50178409683231.9580062142325020.01346727683200.084019551
#Sta/Elev= 30
       0 2889.61    19.4  2883.8    27.4 2882.92    35.5  2878.4    39.5 2877.28
    61.1  2873.4    71.6  2870.2   103.7 2863.83   115.8 2858.89   119.8 2855.95
   135.8 2841.07   143.9 2835.69   147.9 2834.09   151.9 2833.83     168 2834.17
     184 2829.21     188 2828.91   200.22829.406   204.1 2831.21   232.2 2852.33
   240.2 2859.38   244.2 2861.86   256.3 2864.26   268.3 2864.74   276.4  2866.3
   290.1 2867.11   292.4 2867.82   296.4 2870.78   300.5 2872.55   368.9 2899.52
#Mann= 3 ,-1,0
       0      .1       0     184    .045       0   200.2      .1       0
Bank Sta=184,200.2
XS Rating Curve= 0 ,0
Exp/Cntr(USF)=0,0
Exp/Cntr=0.3,0.1

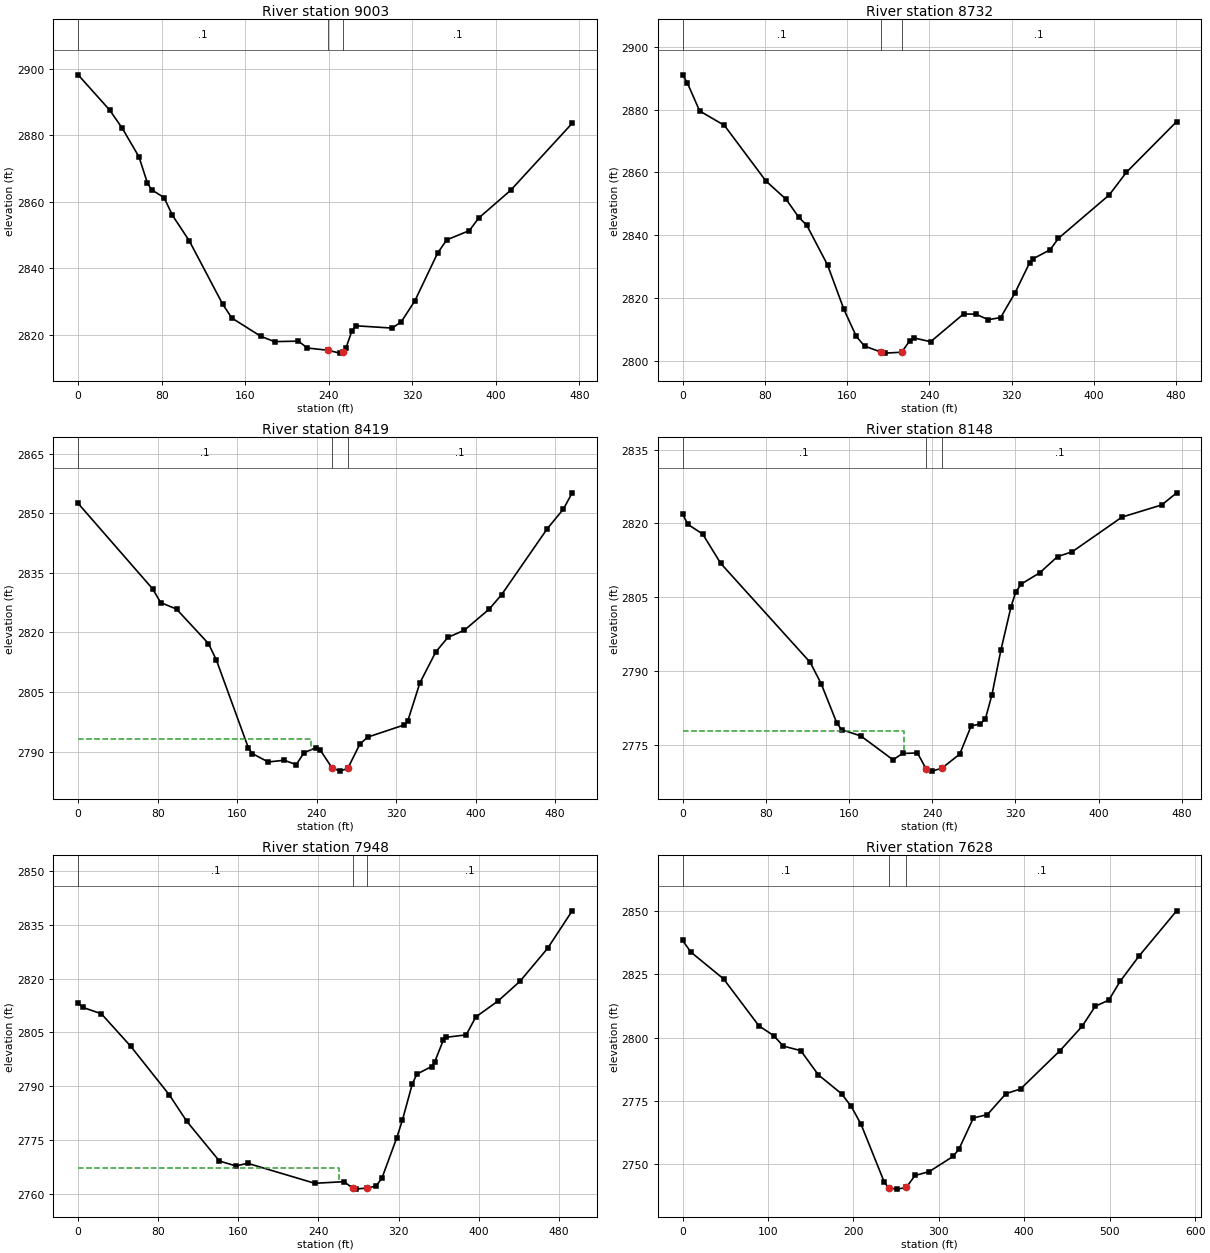
Type RM Length L Ch R = 1 ,9003    ,278.9,271.2,264
XS GIS Cut Line= 4
2325474.37402226 683018.214801532325333.75349286683010.090059831
2325233.75667195682887.593954223 2325073.7617585682956.341768595
#Sta/Elev= 30
       0 2898.26    30.2 2887.66    42.3 2882.17    58.3 2873.55    66.3 2865.74
    70.3 2863.68    82.3 2861.31    90.3 2855.98   106.4 2848.32   138.4 2829.23
   147.2 2825.05     175 2819.54   188.1 2817.95   210.9  2818.1   219.5 2816.03
   239.3 2815.35   250.5 2814.49   253.5 2814.86   256.3  2815.9     262 2821.02
     266 2822.72   300.7 2822.03   309.4  2823.9   322.5 2830.27   344.2  2844.6
   352.9 2848.57   374.7 2851.39   383.4 2855.11   414.1 2863.49   473.1 2883.68
#Mann= 3 ,-1,0
       0      .1       0   239.3    .045       0   253.5      .1       0
Bank Sta=239.3,253.5
XS Rating Curve= 0 ,0
Exp/Cntr(USF)=0,0
Exp/Cntr=0.3,0.1

Type RM Length L Ch R = 1 ,8732    ,312.6,313.6,312.7
XS GIS Cut Line= 3
2325528.74729362682699.4749348962325154.38419536682726.974060644
2325053.13741419682755.723146655
#Sta/Elev= 30
       0 2891.02     4.6  2888.5    16.6 2879.55    40.7 2874.96      81 2857.33
   100.8 2851.46   112.9 2845.85   120.9 2843.19     141 2830.65     157 2816.49
     169 2807.94     177 2804.88   192.7    2803   197.1 2802.63   213.1 2802.92
   221.2 2806.64   225.2 2807.44   241.3 2806.26   273.3 2815.06   285.3 2815.01
   297.4 2813.25   309.4 2813.92   323.5 2821.85   337.5 2831.26   340.7 2832.54
   357.5 2835.46   365.6 2839.09   415.1 2852.89   431.7 2860.05   480.6 2876.16
#Mann= 3 ,-1,0
       0      .1       0   192.7    .045       0   213.1      .1       0
Bank Sta=192.7,213.1
XS Rating Curve= 0 ,0
Exp/Cntr(USF)=0,0
Exp/Cntr=0.3,0.1

Type RM Length L Ch R = 1 ,8419    ,266.1,271,277.1
XS GIS Cut Line= 3
2325546.87171741682400.1094523122325181.88332111682428.858538322
2325055.63733472682463.857425638
#Sta/Elev= 30
       0 2852.47    74.9 2830.98      83 2827.53      99 2825.87   131.1 2817.21
   139.1 2813.05   171.2 2791.01   175.2 2789.52   191.3  2787.4   207.3 2787.84
   219.4 2786.73   227.4 2789.76   239.4 2790.99   243.4 2790.48   255.5  2785.9
   263.5  2785.1   271.3 2785.79   283.6 2791.96   291.6 2793.68   327.7 2796.69
   331.7 2797.75   343.8 2807.28   359.8 2815.08     372 2818.75   388.6 2820.56
   413.6 2825.87     426 2829.48   472.1 2846.13   488.3 2851.06   497.1 2855.13
#Mann= 3 ,-1,0
       0      .1       0   255.5    .045       0   271.3      .1       0
#XS Ineff= 2 , 0
           234.6 2793.07
Permanent Ineff=
       F       F
Bank Sta=255.5,271.3
XS Rating Curve= 0 ,0
Exp/Cntr(USF)=0,0
Exp/Cntr=0.3,0.1

Type RM Length L Ch R = 1 ,8148    ,193.3,199.2,198.9
XS GIS Cut Line= 2
2325508.12294931682304.4874923212325123.13518883682026.371334179
#Sta/Elev= 30
       0 2821.91     5.2  2819.8    19.3 2817.86    36.7 2811.88   122.7 2791.75
   133.2 2787.43   148.4 2779.36   152.9 2778.08   171.4 2776.79   202.3 2771.94
   211.5 2773.23   225.8 2773.34   233.9 2770.17   240.1 2769.64   249.5 2770.28
   266.4 2773.09   277.4 2778.83   286.1 2779.22   291.1 2780.29   297.4 2785.19
     306 2794.27   315.7 2803.05   320.3  2806.1   325.6 2807.69   343.3 2809.97
   360.4 2813.26   374.5 2814.24   422.3 2821.29   460.7 2823.78   474.9 2826.23
#Mann= 3 ,-1,0
       0      .1       0   233.9    .045       0   249.5      .1       0
#XS Ineff= 2 , 0
          213.11 2777.76
Permanent Ineff=
       F       F
Bank Sta=233.9,249.5
XS Rating Curve= 0 ,0
Exp/Cntr(USF)=0,0
Exp/Cntr=0.3,0.1

Type RM Length L Ch R = 1 ,7948    ,321.4,320.7,319.1
XS GIS Cut Line= 3
2325538.66140208682230.4995300972325336.79281988681890.510339015
2325269.29496577681819.262604119
#Sta/Elev= 30
       0 2813.14     4.9 2811.95    23.2 2810.19    52.7 2801.08    91.1 2787.59
   108.5 2780.24   141.1 2769.17   157.5 2767.81   169.4 2768.53   236.3 2762.97
   265.5 2763.41   274.2 2761.65   277.2 2761.34   288.8 2761.66   297.6 2762.21
   303.4 2764.38   318.3 2775.67   323.9 2780.58   333.9 2790.75   338.4 2793.38
     353  2795.5     356 2796.69   364.7 2802.81   367.6 2803.64   387.6 2804.31
   397.2  2809.3   419.6 2813.79   441.3 2819.23   468.9 2828.41   493.5 2838.87
#Mann= 3 ,-1,0
       0      .1       0   274.2    .045       0   288.8      .1       0
#XS Ineff= 2 , 0
          260.88 2767.24
Permanent Ineff=
       F       F
Bank Sta=274.2,288.8
XS Rating Curve= 0 ,0
Exp/Cntr(USF)=0,0
Exp/Cntr=0.3,0.1

Type RM Length L Ch R = 1 ,7628    ,104.8,104.2,103.6
XS GIS Cut Line= 2
2325818.37769109682028.735831663 2325454.4965603681579.123544406
#Sta/Elev= 30
       0 2838.31     9.7 2833.72      48 2823.15    89.4 2804.63   106.5 2800.82
     118 2796.64   138.4 2794.85     159  2785.3   186.1 2777.86   197.5 2772.84
   208.9 2765.85   236.1 2743.05   241.3 2740.69   251.5 2740.25   261.9 2740.92
   272.2 2745.65   288.5 2747.11   316.9 2753.19   323.6 2756.07   340.5 2768.32
   356.8 2769.62   378.6  2777.9   395.7 2779.75     442  2794.9   467.7 2804.43
   483.1 2812.34     499 2814.78   512.2 2822.16   534.6 2832.25   578.4 2849.98
#Mann= 3 ,-1,0
       0      .1       0   241.3    .045       0   261.9      .1       0
Bank Sta=241.3,261.9
XS Rating Curve= 0 ,0
Exp/Cntr(USF)=0,0
Exp/Cntr=0.3,0.1

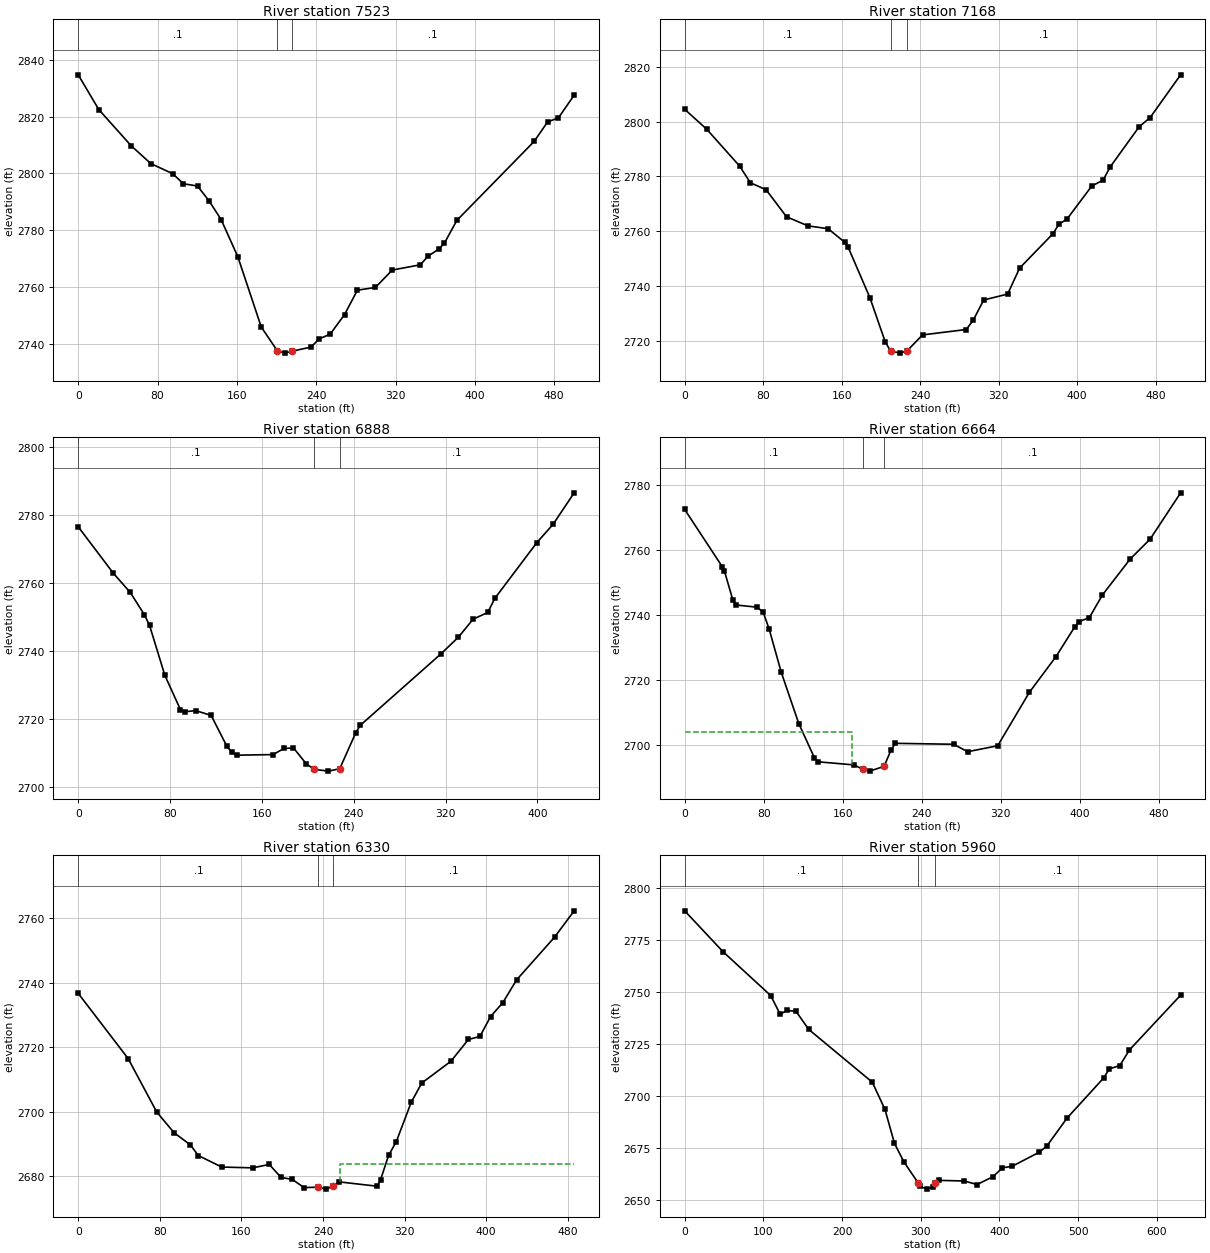
Type RM Length L Ch R = 1 ,7523    ,354.1,355.3,354.2
XS GIS Cut Line= 2
2325882.40047395681918.6344448952325540.53634248681553.646048586
#Sta/Elev= 30
       0 2834.75    20.8  2822.5    53.5 2809.73    73.2 2803.49    95.2 2799.94
   106.1 2796.39   120.3 2795.58     132 2790.34   144.1 2783.78   160.9 2770.72
   184.6 2745.92   200.7 2737.59   208.1 2736.73   215.7 2737.41   234.7 2738.86
   243.1 2741.75   254.1 2743.42   268.6 2750.33   281.5 2758.89   299.7 2759.87
   316.7 2765.99     345 2767.84   352.8  2770.9   363.7 2773.39   369.2 2775.42
   381.8 2783.47   459.7 2811.27   473.3 2818.14   484.3 2819.62   500.1 2827.59
#Mann= 3 ,-1,0
       0      .1       0   200.7    .045       0   215.7      .1       0
Bank Sta=200.7,215.7
XS Rating Curve= 0 ,0
Exp/Cntr(USF)=0,0
Exp/Cntr=0.3,0.1

Type RM Length L Ch R = 1 ,7168    ,274.3,280.3,282.7
XS GIS Cut Line= 2
2326134.63040162681673.4278165212325786.94293371681306.688980517
#Sta/Elev= 30
       0 2804.54    22.4 2797.28    55.9 2783.83      67 2777.69      83 2775.14
   103.8 2765.27   125.7 2761.95   146.2 2760.91   163.2 2755.93   166.4  2754.3
   188.7 2735.77   204.3 2719.66   209.8 2716.21   219.8 2715.46   226.72716.317
   242.4 2722.12     287 2724.09   294.3 2727.66   304.7 2734.87   329.1 2737.03
   341.4 2746.56   375.2 2759.04   381.5 2762.61   389.5 2764.38     415 2776.57
   426.3 2778.61   433.8 2783.57   463.1 2798.13   474.4 2801.54   505.4 2817.13
#Mann= 3 ,-1,0
       0      .1       0   209.8    .045       0   226.7      .1       0
Bank Sta=209.8,226.7
XS Rating Curve= 0 ,0
Exp/Cntr(USF)=0,0
Exp/Cntr=0.3,0.1

Type RM Length L Ch R = 1 ,6888    ,223.4,224.1,225
XS GIS Cut Line= 3
2326237.50778938681488.6295459112326116.53160192681248.582307799
2325989.84000402681145.704920037
#Sta/Elev= 30
       0 2776.59    30.7 2762.86    45.3 2757.27    57.6 2750.71    62.1 2747.58
    75.5  2732.8      89 2722.75    93.4 2722.13   102.4 2722.43   115.8 2721.02
   129.3 2712.06   133.8 2710.12   138.2 2709.31   169.6 2709.48   179.3 2711.28
   187.5 2711.46   198.5 2706.83   205.4 2705.13     218 2704.61   227.8 2705.32
   241.8 2715.93   245.7  2718.1   315.6 2739.04   331.2 2744.07     344 2749.38
   356.7 2751.34     363 2755.54   399.4 2771.88   413.7 2777.34     432 2786.59
#Mann= 3 ,-1,0
       0      .1       0   205.4    .045       0   227.8      .1       0
Bank Sta=205.4,227.8
XS Rating Curve= 0 ,0
Exp/Cntr(USF)=0,0
Exp/Cntr=0.3,0.1

Type RM Length L Ch R = 1 ,6664    ,337,334,325.1
XS GIS Cut Line= 3
2326414.68551275681374.3213372862326326.09665106681159.993446115
2326116.53160192680989.483701583
#Sta/Elev= 30
       0  2772.6      38    2755    40.2 2753.69    48.8 2744.66    51.8 2743.19
    73.2 2742.51    79.4 2741.01    85.5 2735.81    97.7 2722.53   115.5 2706.69
   131.4  2696.1   135.4 2694.89   171.2 2693.95   180.4 2692.61   187.3 2692.03
   201.9  2693.5     209 2698.58   213.3 2700.59   272.2  2700.3   286.5 2698.01
   316.9 2699.84     349  2716.3   375.8 2727.24   394.8 2736.39   399.4  2738.1
   409.7 2739.29   422.9 2746.26     451 2757.32   471.3 2763.49   502.1 2777.72
#Mann= 3 ,-1,0
       0      .1       0   180.4    .045       0   201.9      .1       0
#XS Ineff= 2 , 0
          168.91 2703.99
Permanent Ineff=
       F       F
Bank Sta=180.4,201.9
XS Rating Curve= 0 ,0
Exp/Cntr(USF)=0,0
Exp/Cntr=0.3,0.1

Type RM Length L Ch R = 1 ,6330    ,375.9,370.1,360.9
XS GIS Cut Line= 3
2326649.76396135 681112.446931212326364.61764333680816.177619142
2326298.47216731680780.871220843
#Sta/Elev= 30
       0 2736.72    48.9 2716.48      77 2699.85      94 2693.41     110 2689.64
   117.7 2686.34   140.7 2682.76   171.1 2682.51   187.3 2683.57   198.8 2679.54
   209.9 2678.91   221.5 2676.36235.42682676.527   243.3  2675.9249.58232676.857
   256.1 2678.14   293.2  2676.8   296.5 2678.89   304.3 2686.39   311.8 2690.64
   326.5 2702.91   336.8 2708.86   365.4 2715.63   382.5 2722.39   393.8 2723.33
   404.3 2729.53   416.2  2733.8   429.8 2740.92     467 2754.18   486.2 2762.36
#Mann= 3 ,-1,0
       0      .1       0235.4268    .045       0249.5823      .1       0
#XS Ineff= 2 , 0
                          256.36         2683.82
Permanent Ineff=
       F       F
Bank Sta=235.4268,249.5823
XS Rating Curve= 0 ,0
Exp/Cntr(USF)=0,0
Exp/Cntr=0.3,0.1

Type RM Length L Ch R = 1 ,5960    ,378,383.1,381.7
XS GIS Cut Line= 2
2327020.51901846680718.0017060992326395.63414464680636.080823251
#Sta/Elev= 30
       0 2789.21    48.8 2769.52   109.3 2748.48   121.4  2739.4   129.4 2741.31
   141.5 2740.87   157.7 2732.17   238.4 2706.81   254.5 2693.73   266.6 2677.38
   278.7 2668.41   296.6 2658.46   298.9 2656.76   307.8  2655.4     315 2656.38
   318.5 2658.45   323.1 2659.61   355.4 2659.31   371.5 2657.62   391.7 2661.37
   403.8 2665.67   415.9 2666.34   450.4 2673.11   460.2 2676.13   486.1 2689.66
   532.5 2708.88   539.6 2713.22     553 2714.83   565.1 2722.29   630.2 2748.65
#Mann= 3 ,-1,0
       0      .1       0   296.6    .045       0   318.5      .1       0
Bank Sta=296.6,318.5
XS Rating Curve= 0 ,0
Exp/Cntr(USF)=0,0
Exp/Cntr=0.3,0.1

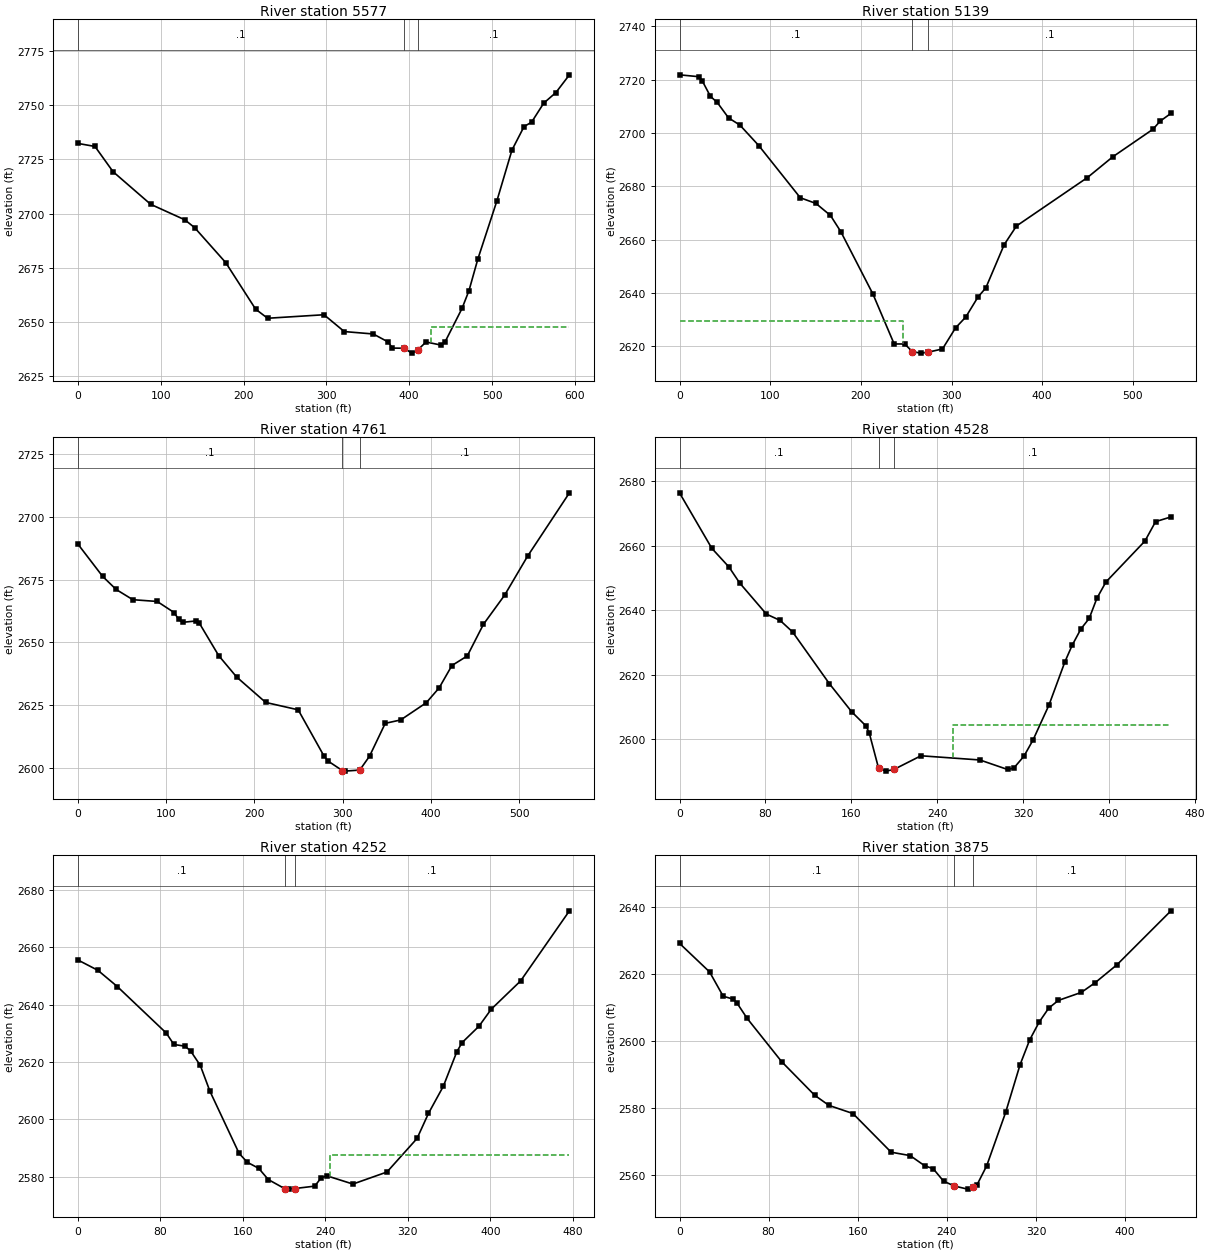
Type RM Length L Ch R = 1 ,5577    ,436.2,438.1,437.5
XS GIS Cut Line= 2
2326985.32667939680514.9606122392326464.08124806680231.190484328
#Sta/Elev= 30
       0  2732.3    20.5 2730.91    42.3  2719.3    87.8 2704.26     129 2697.13
   140.8 2693.54   178.4 2677.42   214.5 2655.98     229 2651.78   297.1  2653.4
   321.6 2645.65   356.6 2644.54   374.8 2640.81   379.6 2638.05   393.8 2637.97
   403.2 2635.72   410.62637.269   420.3 2640.85   438.5 2639.42   443.1 2640.74
   463.8 2656.31   472.2 2664.52   482.8 2678.92   505.7 2705.59   524.1 2729.24
   538.7 2740.07   547.8 2742.09   562.5 2750.88   577.2 2755.75   593.5  2763.9
#Mann= 3 ,-1,0
       0      .1       0   393.8    .045       0   410.6      .1       0
#XS Ineff= 2 , 0
                          426.34         2647.74
Permanent Ineff=
       F       F
Bank Sta=393.8,410.6
XS Rating Curve= 0 ,0
Exp/Cntr(USF)=0,0
Exp/Cntr=0.3,0.1

Type RM Length L Ch R = 1 ,5139    ,376.1,377.7,376.9
XS GIS Cut Line= 4
2327168.16712126 680103.404571062327000.99136615680055.395123437
2326826.09980695679939.6580622052326668.35447905679927.655700299
#Sta/Elev= 30
       0 2721.86    21.2 2721.16      25 2719.66    34.1 2713.79    41.6 2711.51
    54.1 2705.71    66.6 2703.01    87.4 2695.33   133.2 2675.76   150.5 2673.62
   166.5 2669.11   177.9 2663.03   213.3 2639.64   236.7 2620.93   248.3 2620.92
   256.9 2618.03     266 2617.49   273.92617.826     290 2619.06   304.4 2626.96
   315.7 2631.04   329.1 2638.51   337.8 2641.97     358 2658.15   371.6 2665.18
   449.8 2683.33   477.8 2691.12     522 2701.43     530 2704.48   541.9  2707.4
#Mann= 3 ,-1,0
       0      .1       0   256.9    .045       0   273.9      .1       0
#XS Ineff= 2 , 0
          246.99 2629.49
Permanent Ineff=
       F       F
Bank Sta=256.9,273.9
XS Rating Curve= 0 ,0
Exp/Cntr(USF)=0,0
Exp/Cntr=0.3,0.1

Type RM Length L Ch R = 1 ,4761    ,231.9,232.6,234.2
XS GIS Cut Line= 3
2327265.04332807679811.9186390672326886.11161648679577.015270343
2326778.09035933679550.438611837
#Sta/Elev= 30
       0 2689.11      28 2676.26    43.3 2671.06    62.2 2666.99    89.8 2666.29
   109.3  2661.8     114 2659.11   118.7 2657.97   133.4 2658.51   137.5 2657.67
   159.5 2644.71   179.8 2636.19   212.8 2626.04   249.6  2623.1   278.7 2604.79
   283.4 2602.69   299.72598.877   302.2 2598.66   319.42599.076   330.5 2604.61
   348.3 2617.71   365.8 2619.06   394.8 2625.91   409.4 2631.84   423.9 2640.76
   441.3 2644.57   459.6 2657.16   483.7 2668.83   509.6  2684.3   557.1 2709.59
#Mann= 3 ,-1,0
       0      .1       0   299.7    .045       0   319.4      .1       0
Bank Sta=299.7,319.4
XS Rating Curve= 0 ,0
Exp/Cntr(USF)=0,0
Exp/Cntr=0.3,0.1

Type RM Length L Ch R = 1 ,4528    ,277.6,276.1,277
XS GIS Cut Line= 2
2327317.33933352679595.018813201 2326948.6953607 679324.10835876
#Sta/Elev= 30
       0 2676.31    30.1 2659.13    46.1 2653.34      56 2648.42    80.9 2638.78
    93.7 2636.82   105.2 2633.29   139.5 2617.26   160.3 2608.55   173.8 2604.11
   176.7 2601.93   185.3 2591.13   192.2 2590.19   199.7 2590.72   224.8 2594.94
   279.7 2593.64   305.4  2590.7   311.2 2591.13   320.6 2594.78   329.1 2599.81
     344 2610.67   358.8 2624.02   365.5  2629.1   373.7  2634.2   381.4 2637.44
   388.6  2643.7     397 2648.72   433.3 2661.39   443.2 2667.39   457.5 2668.85
#Mann= 3 ,-1,0
       0      .1       0   185.3    .045       0   199.7      .1       0
#XS Ineff= 2 , 0
                          254.66          2604.5
Permanent Ineff=
       F       F
Bank Sta=185.3,199.7
XS Rating Curve= 0 ,0
Exp/Cntr(USF)=0,0
Exp/Cntr=0.3,0.1

Type RM Length L Ch R = 1 ,4252    ,374.8,377.4,384.3
XS GIS Cut Line= 3
2327391.92543965679370.4031832532327121.01498521679115.781648542
2327017.28028588679100.350040377
#Sta/Elev= 30
       0 2655.59    19.3    2652    38.1 2646.35    85.6 2630.13      93 2626.13
     104 2625.52   109.4 2623.78   118.6 2618.85     128  2609.8   156.3 2588.12
   164.3 2585.03   175.3 2582.93   184.6 2579.01   200.4 2575.86   204.4 2575.67
   210.1 2575.87   229.6 2576.71   235.7 2579.51   241.2 2580.34   266.7 2577.44
   299.7 2581.64   328.9 2593.35     340 2602.11   354.4 2611.56   367.4 2623.52
   372.6 2626.79   388.9 2632.47   400.9 2638.45   429.3 2648.28   476.7 2672.75
#Mann= 3 ,-1,0
       0      .1       0   200.4    .045       0   210.1      .1       0
#XS Ineff= 2 , 0
                          244.21         2587.74
Permanent Ineff=
       F       F
Bank Sta=200.4,210.1
XS Rating Curve= 0 ,0
Exp/Cntr(USF)=0,0
Exp/Cntr=0.3,0.1

Type RM Length L Ch R = 1 ,3875    ,428.6,425.2,420.1
XS GIS Cut Line= 3
2327489.65895802679166.3630308582327357.63297706678825.153028113
2327286.47611719678800.290992737
#Sta/Elev= 30
       0 2629.27      27 2620.74    39.2 2613.48    48.4 2612.59    51.5  2611.5
    60.8 2606.83    91.7 2593.94   121.4 2583.89   134.2 2580.87   155.7 2578.45
     190  2566.9   207.1 2565.88     220 2562.87   227.8 2561.95   237.1 2558.24
   246.72556.808   258.6 2555.87   263.6  2556.4   267.2 2557.21   275.8 2562.84
   292.8 2578.78   305.8 2593.07   314.4 2600.44   322.9 2605.76   331.5 2609.93
   340.1 2612.22   360.8 2614.63   373.3 2617.55   392.8 2622.89   441.2 2638.98
#Mann= 3 ,-1,0
       0      .1       0   246.7    .045       0   263.6      .1       0
Bank Sta=246.7,263.6
XS Rating Curve= 0 ,0
Exp/Cntr(USF)=0,0
Exp/Cntr=0.3,0.1

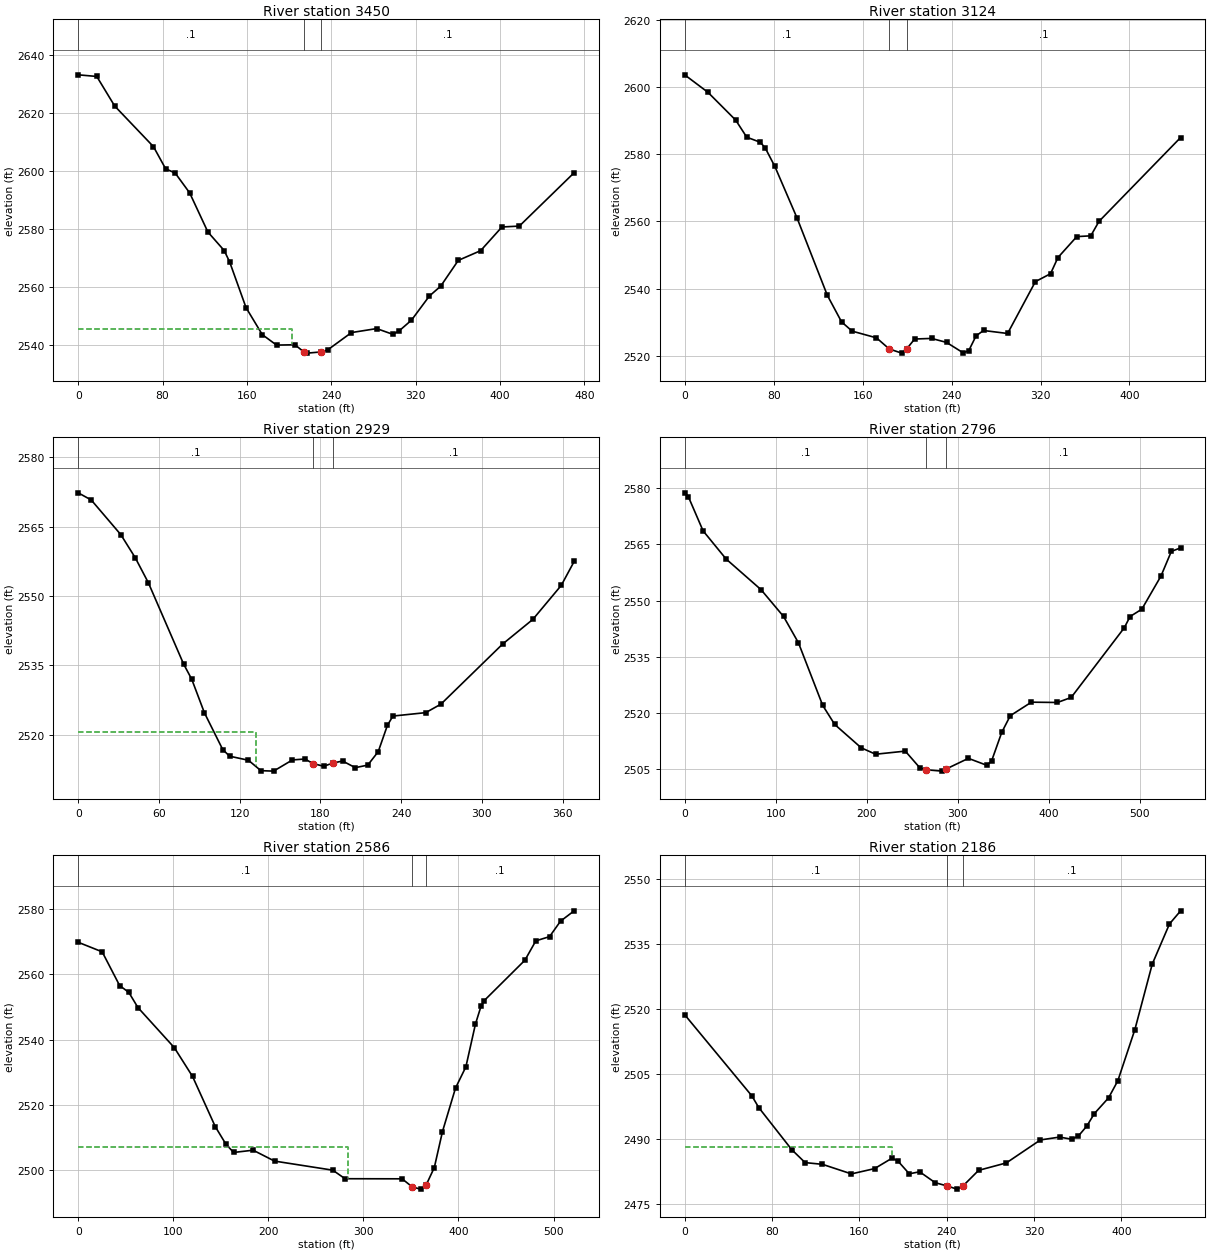
Type RM Length L Ch R = 1 ,3450    ,321.2,326,325
XS GIS Cut Line= 2
2327923.45860975678906.5976267592327559.10119476678609.110513813
#Sta/Elev= 30
       0 2633.09    17.6 2632.53    34.6 2622.35    71.4 2608.35    82.9 2600.75
      92 2599.26   105.7 2592.45     123 2578.97   138.5 2572.58   143.7 2568.61
   159.2 2552.92   174.6 2543.64   188.1 2540.04   205.6 2540.14   213.7 2537.77
   217.3 2537.27   229.9 2537.67   236.5 2538.35   259.2 2544.35   283.1 2545.72
   298.6 2543.72   304.7 2545.03   316.1 2548.62   333.1 2556.94   343.8 2560.32
   360.5  2569.2   381.7 2572.55   401.9  2580.7   418.4 2581.01   470.4 2599.39
#Mann= 3 ,-1,0
       0      .1       0   213.7    .045       0   229.9      .1       0
#XS Ineff= 2 , 0
          202.66 2545.63
Permanent Ineff=
       F       F
Bank Sta=213.7,229.9
XS Rating Curve= 0 ,0
Exp/Cntr(USF)=0,0
Exp/Cntr=0.3,0.1

Type RM Length L Ch R = 1 ,3124    ,194.7,195,195.8
XS GIS Cut Line= 2
2328092.87143366678701.9392669942327826.24753704 678344.44034452
#Sta/Elev= 30
       0 2603.66    20.9 2598.46    45.9 2590.16    55.8 2585.09    68.1 2583.56
    72.5 2581.84    81.1 2576.37   101.1 2560.98   128.3 2537.98   141.1 2530.07
   150.6 2527.32   172.5 2525.32     184    2522   195.2 2520.77  199.58    2522
   206.8 2524.97     222 2525.15   235.5 2523.96   250.4 2520.87   255.4 2521.47
   262.1 2525.94   268.8 2527.51   290.4 2526.62   315.4 2542.07     329 2544.42
   335.7 2549.25   352.6 2555.47   365.2 2555.71   372.6 2560.01     446 2584.99
#Mann= 3 ,-1,0
       0      .1       0     184    .045       0  199.58      .1       0
Bank Sta=184,199.58
XS Rating Curve= 0 ,0
Exp/Cntr(USF)=0,0
Exp/Cntr=0.3,0.1

Type RM Length L Ch R = 1 ,2929    ,142.1,132.9,122.2
XS GIS Cut Line= 3
2328203.31710207678569.4933442112328081.94246081678368.159057515
2327991.32152932678270.157235682
#Sta/Elev= 30
       0 2572.28     9.7 2570.73    31.7 2563.23    42.4 2558.25    52.1 2552.87
    78.3  2535.3    84.4 2531.98    93.8 2524.74   107.4 2516.81   112.5 2515.37
   126.5 2514.49   135.8 2512.24   145.2 2512.14   159.2 2514.56   168.6 2514.76
   174.4 2513.78   182.5 2513.19     189 2513.86   196.5 2514.33   205.9 2512.89
   215.2 2513.44     223 2516.36   229.8 2522.03   233.9 2524.04   258.3 2524.78
   269.6 2526.62   315.4 2539.59   337.9 2544.93     359 2552.27   368.6 2557.45
#Mann= 3 ,-1,0
       0      .1       0   174.4    .045       0     189      .1       0
#XS Ineff= 2 , 0
          131.88 2520.64
Permanent Ineff=
       F       F
Bank Sta=174.4,189
XS Rating Curve= 0 ,0
Exp/Cntr(USF)=0,0
Exp/Cntr=0.3,0.1

Type RM Length L Ch R = 1 ,2796    ,205.2,209.8,216.3
XS GIS Cut Line= 4
 2328410.0767126678522.761149975 2328337.2052296678389.877857448
2328078.29713706678339.2964751322327991.70866903678243.277579887
#Sta/Elev= 30
       0 2578.77       4 2577.76    20.2 2568.63    45.5 2561.11    83.9 2552.92
   108.6 2545.77     125 2538.72   151.6 2522.04   164.8 2516.95   193.9 2510.72
   209.7 2509.01   242.3 2509.84   258.3 2505.38   265.5 2504.86   282.6  2504.5
   287.1 2505.06   311.6 2507.91   331.9 2506.05   337.1 2507.22   348.2 2514.82
   357.6 2519.29   380.8  2522.9   409.4 2522.82   424.5 2524.16   482.8 2542.75
   489.2 2545.76   502.1 2547.72   523.1 2556.55   534.5 2563.14   544.7 2564.08
#Mann= 3 ,-1,0
       0      .1       0   265.5    .045       0   287.1      .1       0
Bank Sta=265.5,287.1
XS Rating Curve= 0 ,0
Exp/Cntr(USF)=0,0
Exp/Cntr=0.3,0.1

Type RM Length L Ch R = 1 ,2586    ,399.7,399.9,397.4
XS GIS Cut Line= 2
2328454.73335463 678469.563144572328167.45753979678034.093558104
#Sta/Elev= 30
       0 2569.72    25.2  2566.8    43.6 2556.48    53.2 2554.42    62.8 2549.78
   101.1 2537.51   120.3  2528.7   144.2 2513.37   155.1 2508.15   163.4 2505.48
     184 2506.18   206.5 2502.85   267.8 2500.07   280.7 2497.46   340.7 2497.43
   351.5 2494.93   360.1 2494.28   365.9 2495.48   374.6 2500.88   383.2 2511.89
   396.9 2525.17   407.8 2531.65   417.9 2544.76   423.7 2550.15   426.9 2551.84
   469.9 2564.24   481.4 2570.16   495.8 2571.44   507.4 2576.18   521.7 2579.33
#Mann= 3 ,-1,0
       0      .1       0   351.5    .045       0   365.9      .1       0
#XS Ineff= 2 , 0
          284.15  2507.2
Permanent Ineff=
       F       F
Bank Sta=351.5,365.9
XS Rating Curve= 0 ,0
Exp/Cntr(USF)=0,0
Exp/Cntr=0.3,0.1

Type RM Length L Ch R = 1 ,2186    ,421,419.9,421
XS GIS Cut Line= 2
 2328784.5073098678296.4680065582328486.72099368677953.521088754
#Sta/Elev= 30
       0 2518.65    61.5  2499.9    67.9 2497.17    98.1 2487.45   110.3 2484.47
   126.2 2484.07   152.7 2481.86   173.9 2483.08   189.8 2485.48   195.1 2484.89
   205.7 2481.88   215.2 2482.35   229.4 2479.83   240.7 2479.05   249.3 2478.34
   254.9 2479.08   269.2 2482.68   294.6  2484.4   325.8 2489.71   343.4 2490.37
   354.4 2489.87   360.5 2490.59   368.3 2492.92   375.2  2495.8   388.2 2499.43
   396.7 2503.39   412.3 2515.21   428.2 2530.34     444 2539.63   454.2 2542.66
#Mann= 3 ,-1,0
       0      .1       0   240.7    .045       0   254.9      .1       0
#XS Ineff= 2 , 0
          190.22 2488.19
Permanent Ineff=
       F       F
Bank Sta=240.7,254.9
XS Rating Curve= 0 ,0
Exp/Cntr(USF)=0,0
Exp/Cntr=0.3,0.1