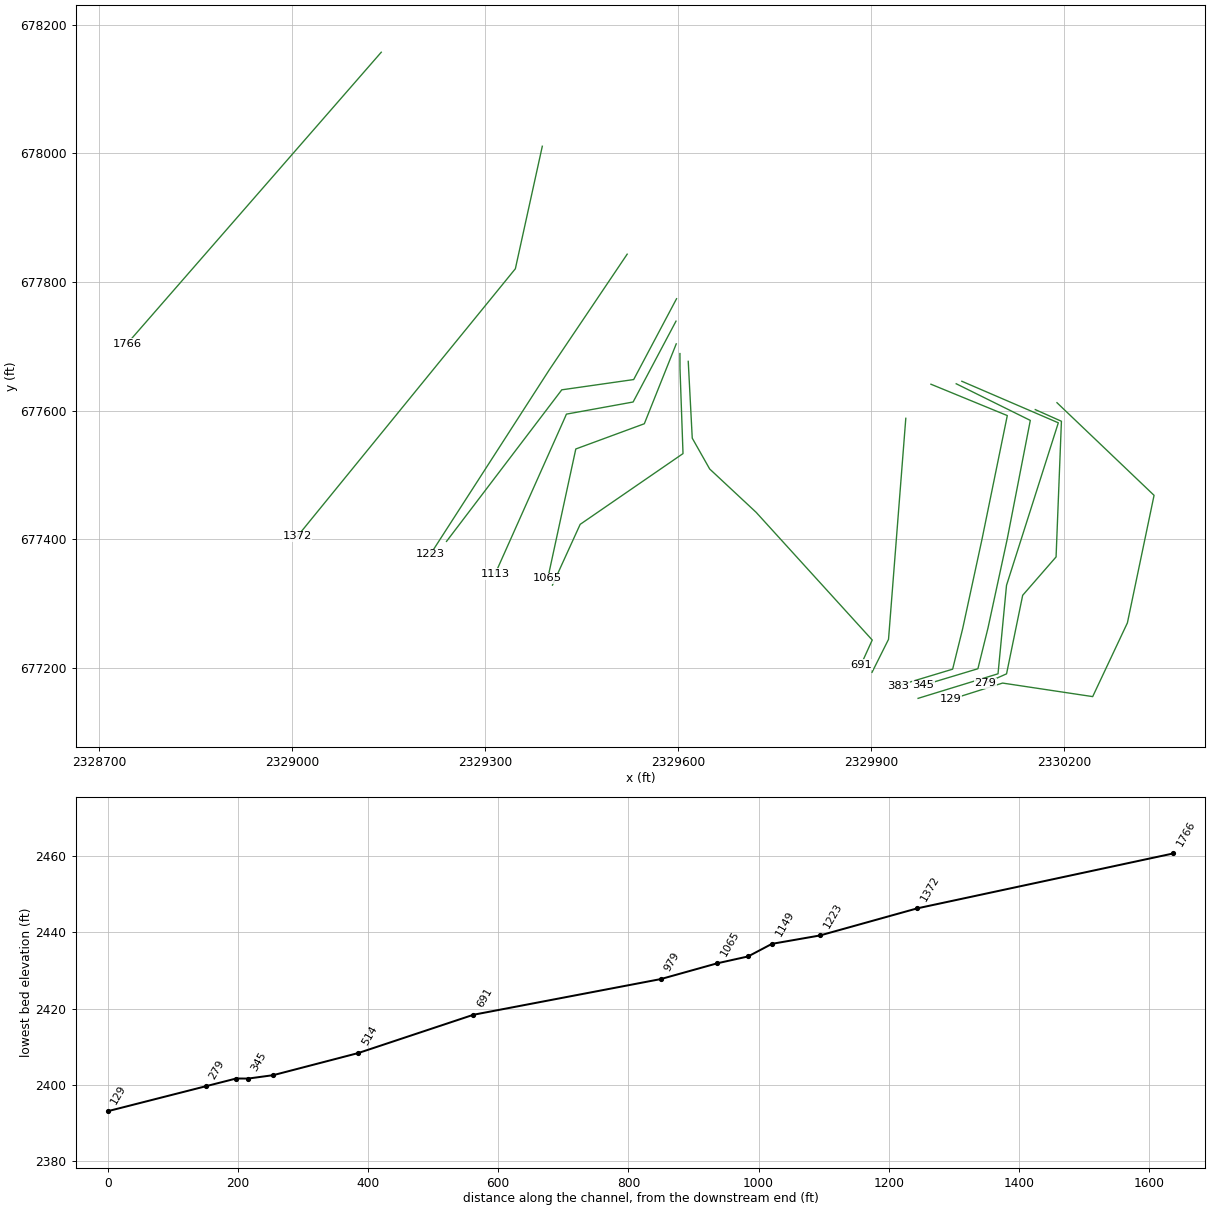
HEC-RAS study UPPRPNDLCK.prj: UPPRPNDLCK

--- UPPRPNDLCK.g01 (geometry) --- (continued)

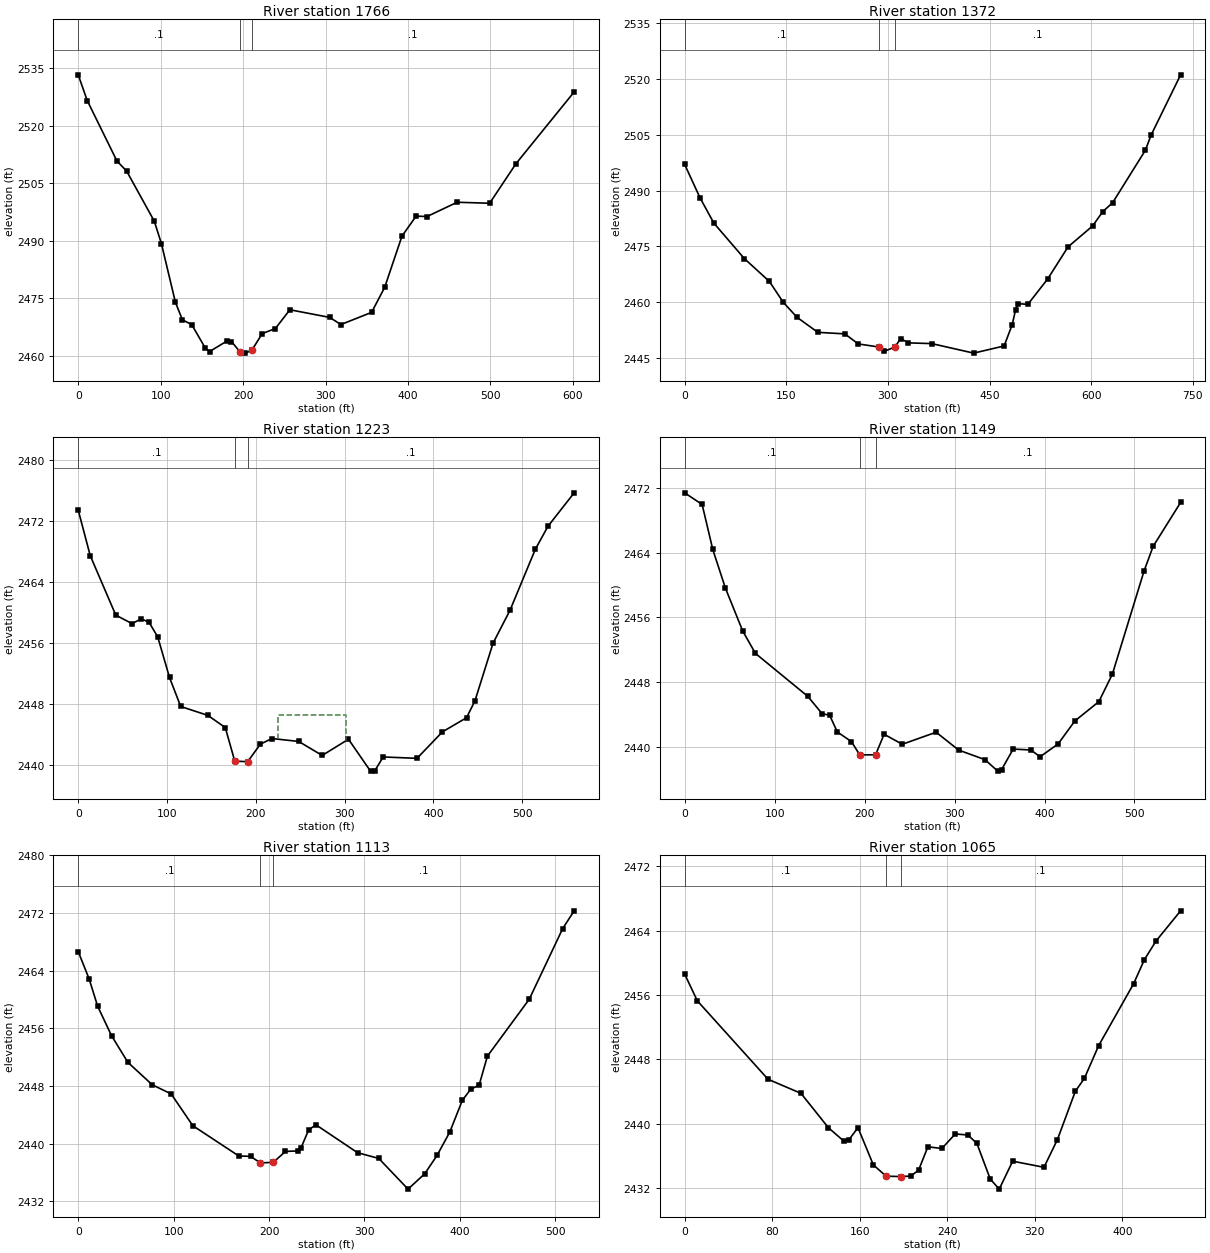
Type RM Length L Ch R = 1 ,1766    ,393,393.8,394.8
XS GIS Cut Line= 2
 2329138.2390407678157.4091666552328742.92315254677703.986605777
#Sta/Elev= 30
       0 2533.23    10.9 2526.54      47 2510.77    58.7 2508.16    92.3 2495.09
   100.9 2489.28   117.9 2473.96   126.4  2469.4   137.7 2468.15   154.2 2462.02
   159.5 2461.14   180.7 2463.91   185.9 2463.74   196.22461.048   202.9 2460.72
   210.82461.527   223.2 2465.81   239.1 2467.12   256.8 2472.02     305 2470.03
   318.7 2468.17   355.9 2471.34   371.8 2477.88   392.7 2491.19   409.9 2496.42
   423.1 2496.31   459.7 2500.03   499.1 2499.77     531 2510.07   601.6 2528.78
#Mann= 3 ,-1,0
       0      .1       0   196.2    .045       0   210.8      .1       0
Bank Sta=196.2,210.8
XS Rating Curve= 0 ,0
Exp/Cntr(USF)=0,0
Exp/Cntr=0.3,0.1

Type RM Length L Ch R = 1 ,1372    ,147,149.2,151.3
XS GIS Cut Line= 3
2329388.67943952678011.2276827412329346.76642969  677820.7140017
2329007.65207744677404.441608625
#Sta/Elev= 30
       0 2497.05    22.6 2488.09    43.1 2481.26    88.1 2471.72     125 2465.59
   145.4 2459.99   165.9 2455.92   196.6 2451.89   236.4 2451.48   256.2 2448.77
   287.3 2447.93   294.2 2446.76   310.3 2447.94   318.8 2450.22   330.2 2449.06
   364.7 2448.86   426.6  2446.3   471.5 2448.23   483.4 2453.95   488.5 2458.02
   492.3 2459.59   506.5 2459.42   535.7 2466.23   565.9 2474.89   602.1  2480.5
   617.2 2484.38   631.6 2486.74   679.9 2500.84   688.4 2504.93     732 2521.15
#Mann= 3 ,-1,0
       0      .1       0   287.3    .045       0   310.3      .1       0
Bank Sta=287.3,310.3
XS Rating Curve= 0 ,0
Exp/Cntr(USF)=0,0
Exp/Cntr=0.3,0.1

Type RM Length L Ch R = 1 ,1223    ,81,73.8,67.2
XS GIS Cut Line= 3
2329520.65634775677843.4179936972329399.46395069677663.451840168
 2329214.4860815677376.417215552
#Sta/Elev= 30
       0 2473.48    13.5 2467.51    42.3 2459.69    60.6 2458.57    71.1 2459.21
    79.8 2458.73    89.5 2456.84   102.8  2451.5   115.4 2447.69     146 2446.52
   165.6 2444.92   176.3  2440.5   190.8 2440.45   205.2 2442.75   218.1 2443.48
   248.2  2443.1   274.7 2441.26   304.3 2443.39   329.1  2439.2   333.9 2439.25
   343.4 2441.06   381.5 2440.88     410 2444.35   437.2 2446.21   446.7 2448.43
   467.1 2456.01   486.2 2460.33   514.7 2468.34     529 2471.37   558.4 2475.75
#Mann= 3 ,-1,0
       0      .1       0   176.3    .045       0   190.8      .1       0
#XS Ineff= 1 ,-1
  225.14  301.64 2446.52
Permanent Ineff=
       F
Bank Sta=176.3,190.8
XS Rating Curve= 0 ,0
Exp/Cntr(USF)=0,0
Exp/Cntr=0.3,0.1

Type RM Length L Ch R = 1 ,1149    ,36.4,36.6,36.9
XS GIS Cut Line= 4
2329597.41775762677774.1425836282329530.75321035677648.452135128
2329418.95120919677632.4804206782329239.73537904677396.792774758
#Sta/Elev= 30
       0 2471.41    19.4 2469.97    31.2 2464.42    45.3 2459.62    64.5 2454.33
    78.6 2451.56   136.9 2446.24     153 2444.07     161 2443.94   169.7 2441.84
   185.3 2440.66  194.622439.007   212.2 2439.02   221.7 2441.56   241.9 2440.32
   279.5 2441.81   304.6  2439.6   333.8 2438.42     348    2437   352.3 2437.19
   365.2 2439.73     385 2439.61     395 2438.77   415.1 2440.36   433.7  2443.2
   460.4 2445.59   475.4 2448.98   510.7 2461.76   520.7 2464.78   551.3 2470.22
#Mann= 3 ,-1,0
       0      .1       0  194.62    .045       0   212.2      .1       0
Bank Sta=194.62,212.2
XS Rating Curve= 0 ,0
Exp/Cntr(USF)=0,0
Exp/Cntr=0.3,0.1

Type RM Length L Ch R = 1 ,1113    ,46.2,47.4,48.5
XS GIS Cut Line= 5
2329596.55646098 677739.241722252329529.89191371 677613.55127375
 2329426.1666402 677594.680496832329423.75575707677589.080792515
2329315.31540218677346.198662299
#Sta/Elev= 30
       0 2466.65    11.4 2462.87    20.4 2459.06      35 2454.96    52.1 2451.28
    77.6 2448.17    97.4 2446.91   120.1  2442.5   168.4 2438.29   180.6 2438.25
190.96472437.338204.44492437.414   217.2 2438.93   230.1    2439   233.5  2439.4
   241.6 2441.95   249.3 2442.61   292.8 2438.75     315 2437.96   345.7  2433.7
   363.2 2435.83   376.3 2438.42   389.5 2441.63   402.6 2446.02   411.4 2447.56
   420.2 2448.12   428.9 2452.15   472.7 2460.03   507.8 2469.84   519.8  2472.3
#Mann= 3 ,-1,0
       0      .1       0190.9647    .045       0204.4449      .1       0
Bank Sta=190.9647,204.4449
XS Rating Curve= 0 ,0
Exp/Cntr(USF)=0,0
Exp/Cntr=0.3,0.1

Type RM Length L Ch R = 1 ,1065    ,84.8,86.8,88.6
XS GIS Cut Line= 4
2329596.93619282677703.9350609022329547.29952071677579.722315578
2329440.76227326677540.4972381082329397.17058273677339.200613703
#Sta/Elev= 30
       0 2458.59    11.6 2455.27    76.2 2445.54   106.3 2443.79   131.4 2439.52
   145.6 2437.85   149.9 2437.99   158.4 2439.53   172.4 2434.92     184 2433.51
   197.4 2433.46   206.7 2433.52   213.8 2434.26   222.3 2437.15   235.1 2436.95
   247.3 2438.75   258.9 2438.62   267.1 2437.57   279.3 2433.15   287.5  2431.9
   299.8 2435.37   328.4 2434.61   340.7 2438.05   357.1 2444.06   365.3 2445.64
   378.4 2449.72   410.3 2457.39   420.2 2460.39   430.8  2462.7   453.3 2466.45
#Mann= 3 ,-1,0
       0      .1       0     184    .045       0   197.4      .1       0
Bank Sta=184,197.4
XS Rating Curve= 0 ,0
Exp/Cntr(USF)=0,0
Exp/Cntr=0.3,0.1

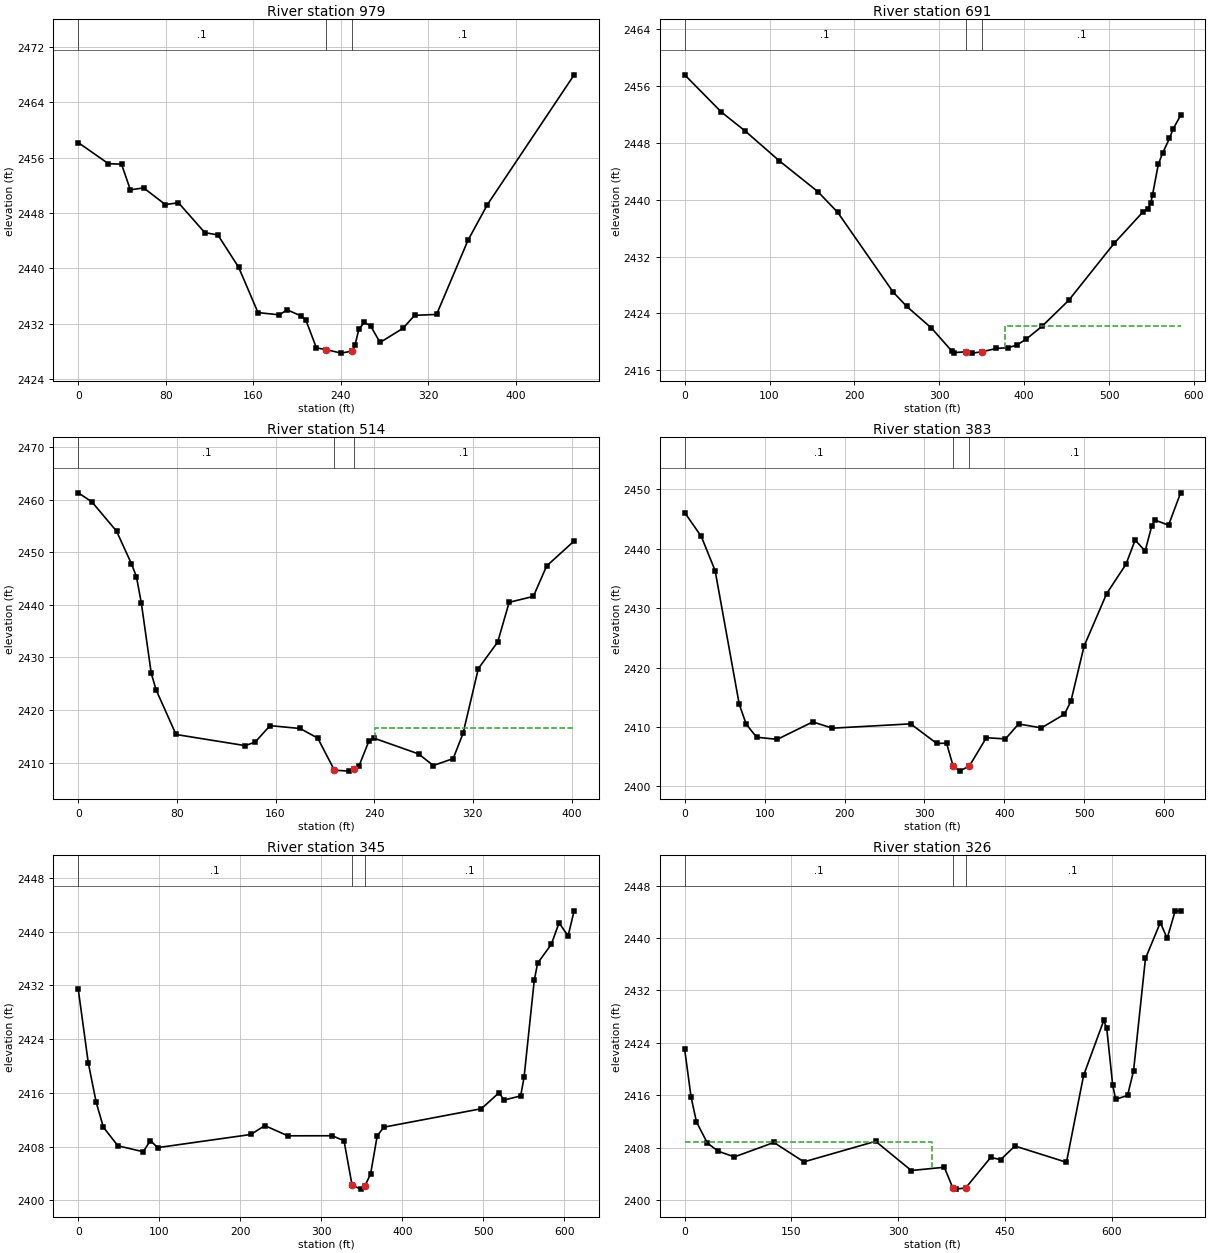
Type RM Length L Ch R = 1 ,979     ,272.5,287.8,304.6
XS GIS Cut Line= 5
2329602.69607284677688.8175469052329602.78765048677665.239055053
2329607.46602723 677533.330098422329447.53673614677423.278648838
2329404.48254936677328.837206872
#Sta/Elev= 30
       0 2458.19    27.6 2455.14    39.6 2455.06    47.7 2451.36    59.8 2451.64
    79.7 2449.23    91.7 2449.49   115.7 2445.18   127.7 2444.84   146.7 2440.17
   164.4 2433.62   183.9 2433.29   191.1 2434.02   203.3 2433.16   208.1 2432.57
   217.8 2428.52   226.4 2428.28   240.5 2427.76   250.1 2428.05     253 2428.88
   256.7 2431.23   261.6 2432.19   267.3 2431.71     276  2429.3     297 2431.35
   307.6 2433.22   327.7 2433.35   356.4 2444.06     374 2449.18   453.5 2467.98
#Mann= 3 ,-1,0
       0      .1       0   226.4    .045       0   250.1      .1       0
Bank Sta=226.4,250.1
XS Rating Curve= 0 ,0
Exp/Cntr(USF)=0,0
Exp/Cntr=0.3,0.1

Type RM Length L Ch R = 1 ,691     ,181.7,176.9,167.8
XS GIS Cut Line= 6
2329615.58694905677676.7428129372329621.83675036677557.302165745
2329648.91922269677509.387022395 2329721.1391489677442.028052757
2329901.68896442677243.4232556822329884.32840524677205.230025476
#Sta/Elev= 30
       0 2457.57    43.3 2452.32    71.6 2449.63   111.6 2445.45   156.8 2441.14
   180.2 2438.22   245.6 2426.99   261.5 2424.98   290.7 2421.93     315 2418.65
   317.2 2418.47   330.9 2418.59   338.8  2418.4   350.2 2418.59   367.2 2419.06
   381.4 2419.17   391.2 2419.54   401.8 2420.32   421.1 2422.19   452.3 2425.82
     506 2433.87   539.9 2438.28   545.9 2438.74   549.1 2439.58   551.1 2440.66
   557.9 2444.96   563.2 2446.62   571.1 2448.61   575.3 2449.94584.2093 2451.86
#Mann= 3 ,-1,0
       0      .1       0   330.9    .045       0   350.2      .1       0
#XS Ineff= 2 , 0
                           377.5         2422.19
Permanent Ineff=
       F       F
Bank Sta=330.9,350.2
XS Rating Curve= 0 ,0
Exp/Cntr(USF)=0,0
Exp/Cntr=0.3,0.1

Type RM Length L Ch R = 1 ,514     ,133.9,130.6,130.1
XS GIS Cut Line= 3
2329953.89213971677588.2129284482329927.01799409677244.473856587
2329901.39380873677193.225485873
#Sta/Elev= 30
       0  2461.3    11.1 2459.58    31.1    2454    43.2 2447.78    47.2 2445.35
    51.2  2440.3    59.2 2426.98    63.2 2423.79    79.3 2415.33   135.4 2413.21
   143.5 2413.89   155.5 2417.01   179.9 2416.47   194.2 2414.64   207.7 2408.54
   219.7 2408.36   223.4 2408.81   227.8 2409.43   235.8 2414.15   239.8 2414.63
   275.9 2411.64   287.9 2409.43     304 2410.74     312 2415.54   324.4 2427.86
   340.1 2432.92   349.4 2440.48     369 2441.59   379.8 2447.39402.0854 2452.14
#Mann= 3 ,-1,0
       0      .1       0   207.7    .045       0   223.4      .1       0
#XS Ineff= 2 , 0
                          240.53         2416.53
Permanent Ineff=
       F       F
Bank Sta=207.7,223.4
XS Rating Curve= 0 ,0
Exp/Cntr(USF)=0,0
Exp/Cntr=0.3,0.1

Type RM Length L Ch R = 1 ,383     ,38.3,38.5,38.4
XS GIS Cut Line= 6
2329992.95926452677641.1927704982330111.70548934677592.444320306
2330072.33174111677399.9504400642330042.33269484677261.204851058
2330026.70819157677198.081857862 2329941.7108938677172.457672505
#Sta/Elev= 30
       0  2446.1    20.8 2442.07    38.1 2436.32    68.3 2413.81      77 2410.46
      90 2408.27   115.9 2407.91   160.3 2410.85   184.8 2409.79   282.8 2410.52
   315.4 2407.22   327.7 2407.27   335.9 2403.42   344.1 2402.56   356.4 2403.45
   377.5 2408.19   401.4 2407.98   417.8  2410.5   446.4 2409.84   475.2 2412.14
   483.3 2414.32   499.8 2423.61   528.1 2432.46   552.2 2437.39   563.7 2441.47
   576.2 2439.62   584.6  2443.9   588.8 2444.82   605.5 2443.97   620.6 2449.42
#Mann= 3 ,-1,0
       0      .1       0   335.9    .045       0   356.4      .1       0
Bank Sta=335.9,356.4
XS Rating Curve= 0 ,0
Exp/Cntr(USF)=0,0
Exp/Cntr=0.3,0.1

Type RM Length L Ch R = 1 ,345     ,19.4,18.5,17.7
XS GIS Cut Line= 6
2330032.26760097677641.9001699282330147.48561703677584.919232643
2330111.64007756677400.6578394942330081.64103129677261.912250488
2330066.01652802677198.7892572922329981.01923025677173.165071935
#Sta/Elev= 30
       0 2431.48    12.4 2420.49    22.2 2414.59    31.1 2410.88      49 2408.12
    80.2 2407.24    89.1  2408.9    98.1 2407.85     213 2409.81   230.3 2411.13
   258.7 2409.61   313.5 2409.62     328 2408.88   337.92402.283   348.5 2401.67
   353.8 2402.16   360.8 2403.92     369 2409.62   377.2  2410.9   497.6 2413.65
   519.5 2416.05   525.2 2414.93     546 2415.55   550.2 2418.34   562.8  2432.8
   566.9 2435.31   583.8 2438.13   593.4 2441.33   604.5 2439.38     612 2443.12
#Mann= 3 ,-1,0
       0      .1       0   337.9    .045       0   353.8      .1       0
Bank Sta=337.9,353.8
XS Rating Curve= 0 ,0
Exp/Cntr(USF)=0,0
Exp/Cntr=0.3,0.1

Type RM Length L Ch R = 1 ,326     ,50.7,46.9,45
XS GIS Cut Line= 5
2330041.04214682677645.7805427052330191.03737817677581.199262538
2330110.48438356677328.4295208052330097.29035858677190.933892061
2329972.98875481677152.740661854
#Sta/Elev= 30
       0    2423     8.9  2415.8    16.5 2411.95    31.9 2408.71      47 2407.47
    69.8  2406.6   125.4  2408.8   167.5 2405.84   268.3 2408.98   318.4 2404.52
   364.8 2405.02  376.84 2401.83   380.8 2401.68   394.8 2401.86     430 2406.52
   443.9 2406.18     464 2408.26   536.4 2405.78   560.5 2419.04   588.8 2427.42
     593 2426.22   601.4 2417.52   605.6 2415.38   622.3 2415.99   630.7 2419.76
   647.4 2436.89   668.3 2442.37   677.9 2439.96   689.2 2444.16   696.8 2444.12
#Mann= 3 ,-1,0
       0      .1       0  376.84    .045       0   394.8      .1       0
#XS Ineff= 2 , 0
          347.82 2408.92
Permanent Ineff=
       F       F
Bank Sta=376.84,394.8
XS Rating Curve= 0 ,0
Exp/Cntr(USF)=0,0
Exp/Cntr=0.3,0.1

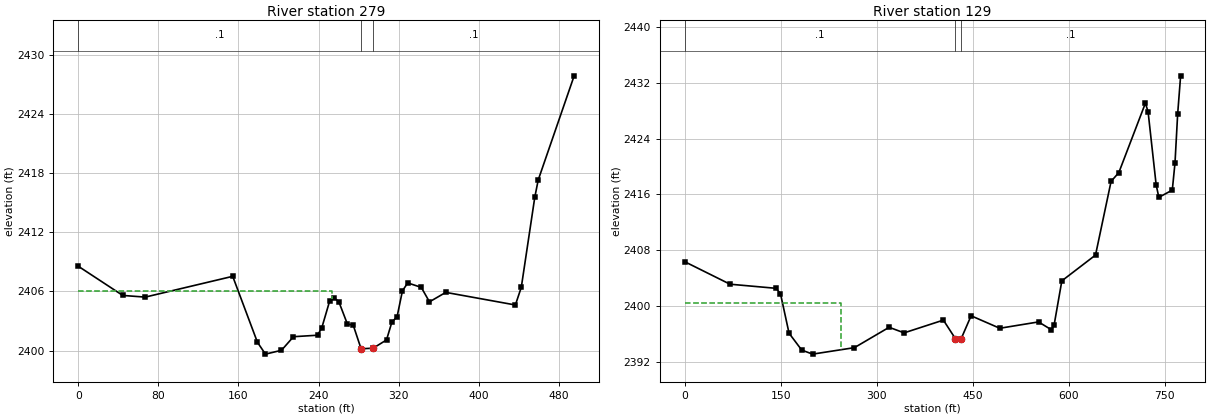
Type RM Length L Ch R = 1 ,279     ,150.8,150.5,147.8
XS GIS Cut Line= 6
2330155.25592619677601.7072594452330195.87963469677583.582835656
 2330187.5538988677372.6327627692330135.61430006677312.947785271
2330110.55572172677190.8441671832330077.75176462677176.264630695
#Sta/Elev= 30
       0 2408.57    44.5  2405.6    66.9 2405.43   154.3 2407.54     179 2400.84
     187 2399.64     203 2400.03     215 2401.41     239 2401.56   243.2 2402.29
     251 2404.99   255.1 2405.38   260.2 2404.98   268.9 2402.68   274.6  2402.6
   282.52400.185   294.5 2400.24   307.9 2401.08   313.2 2402.87   318.5 2403.46
   323.8 2406.07   329.1 2406.87   342.6 2406.42   350.8 2404.95   367.1 2405.91
   436.6 2404.63   442.5 2406.42     456 2415.58   459.4 2417.32   495.3  2427.9
#Mann= 3 ,-1,0
       0      .1       0   282.5    .045       0   294.5      .1       0
#XS Ineff= 2 , 0
          253.19 2406.01
Permanent Ineff=
       F       F
Bank Sta=282.5,294.5
XS Rating Curve= 0 ,0
Exp/Cntr(USF)=0,0
Exp/Cntr=0.3,0.1

Type RM Length L Ch R = 1 ,129     ,,,
XS GIS Cut Line= 6
2330188.95411108 677612.448269072330339.92612388677468.419473026
2330298.47107289677270.0897496592330244.48271984 677155.43679748
2330104.37967399677176.4961279632330023.73661279677150.981939109
#Sta/Elev= 30
       0 2406.36    70.8 2403.13   142.7 2402.54   149.6 2401.77     163  2396.1
   182.8 2393.68   199.8  2393.1   265.1 2394.03   319.3 2396.95   342.7 2396.15
     404 2397.98   422.9  2395.3  431.49 2395.25   447.3  2398.6   492.1 2396.81
   552.6 2397.72   572.8 2396.59   576.9 2397.26     589 2403.61   641.6 2407.31
   665.9 2417.88     678 2419.14   719.5  2429.1   723.7 2427.86   736.3 2417.38
   740.5 2415.59   761.5 2416.63   765.7  2420.5   769.9 2427.57   774.5 2433.02
#Mann= 3 ,-1,0
       0      .1       0   422.9    .045       0  431.49      .1       0
#XS Ineff= 2 , 0
          244.81  2400.4
Permanent Ineff=
       F       F
Bank Sta=422.9,431.49
XS Rating Curve= 0 ,0
Exp/Cntr(USF)=0,0
Exp/Cntr=0.3,0.1
LCMann Table=0

Chan Stop Cuts=-1
Use User Specified Reach Order=0
Composite Channel Slope=5